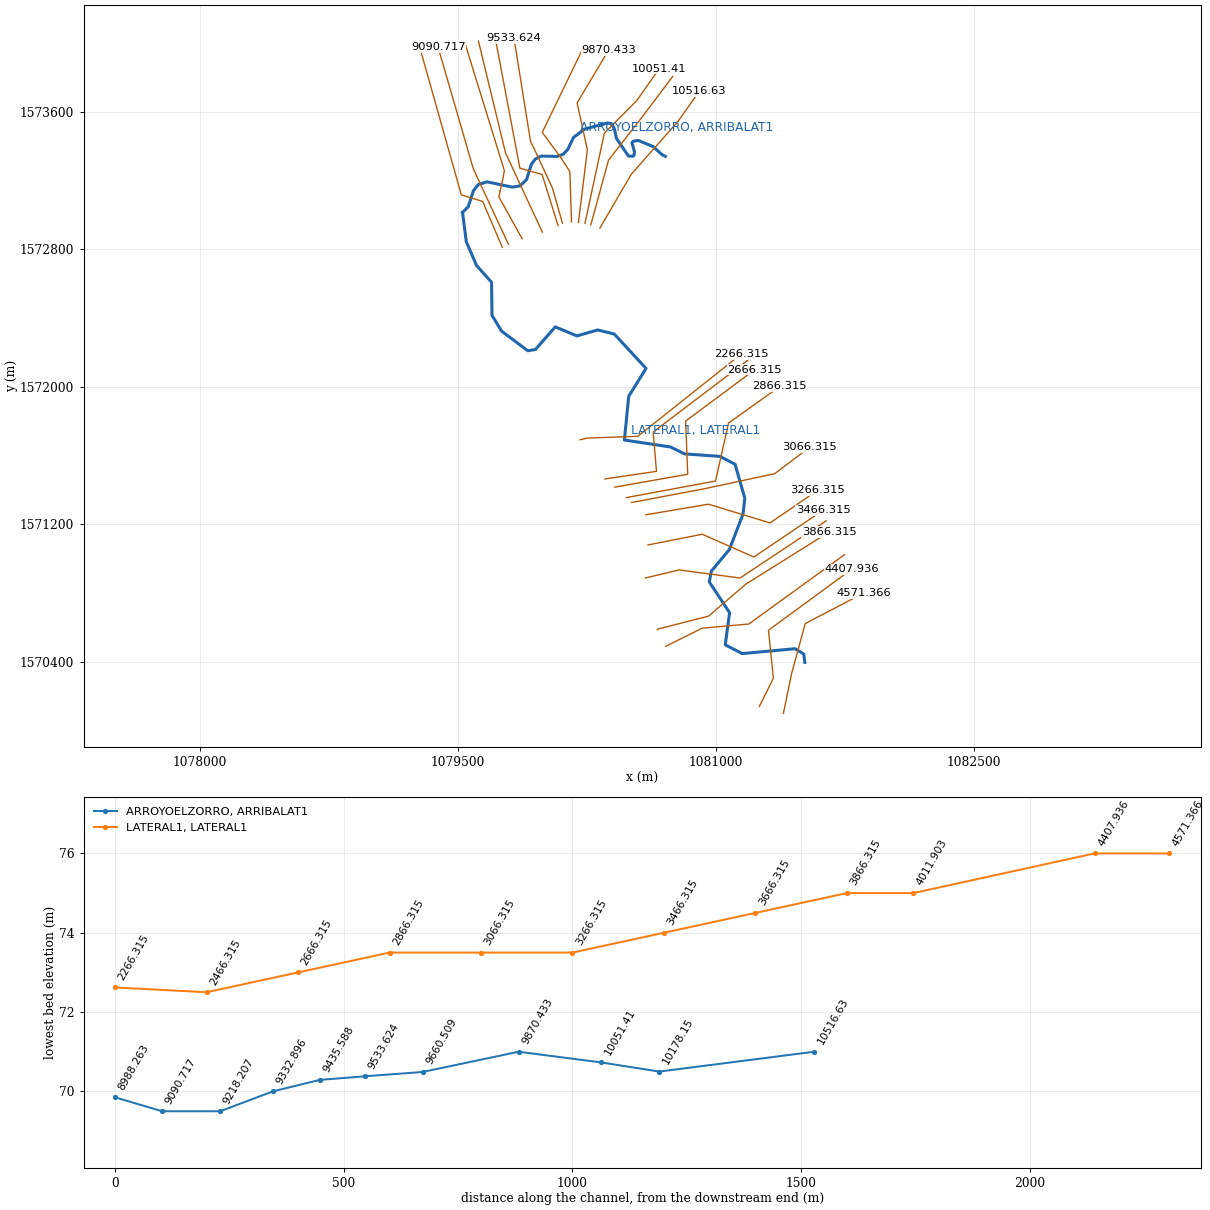
--- HECRAS_v2.prj (project) ---

Proj Title=HECRAS_v2
Current Plan=p02
Default Exp/Contr=0.3,0.1
SI Units
Geom File=g01
Geom File=g02
Flow File=f02
Flow File=f01
Unsteady File=u01
Unsteady File=u02
Plan File=p02
Plan File=p03
Plan File=p01
Plan File=p04
Y Axis Title=Elevation
X Axis Title(PF)=Main Channel Distance
X Axis Title(XS)=Station
BEGIN DESCRIPTION:
Modelo Hec Ras v2
Integracion del terreno natural con el cauce sinuoso disenado
Modelo creado a partir de HecGeoRAS
Elaboro: ECI
Fecha: 20161024
REVISION:
END DESCRIPTION:
DSS File=dss
DSS Export Rating Curves= 0
DSS Export Rating Curve Sorted= 0
DSS Export Volume Flow Curves= 0
DXF OffsetX= 0
DXF OffsetY= 0
DXF ScaleX= 1
DXF ScaleY= 10

--- HECRAS_v2.p02 (plan) ---

Plan Title=HECRAS_v2_Permanente
Program Version=5.03
Geom File=g01
Flow File=f02
Subcritical Flow
K Sum by GR= 0
Std Step Tol= 0.003
Critical Tol= 0.003
Num of Std Step Trials= 20
Max Error Tol= 0.1
Flow Tol Ratio= 0.001
Split Flow NTrial= 30
Split Flow Tol= 0.006
Split Flow Ratio= 0.02
Log Output Level= 0
Friction Slope Method= 1
Unsteady Friction Slope Method= 2
Unsteady Bridges Friction Slope Method= 1
Parabolic Critical Depth
Global Vel Dist= 0 , 0 , 0
Global Log Level= 0
CheckData=True
Encroach Param=-1 ,0,0, 0
Computation Interval=1MIN
Output Interval=1HOUR
Instantaneous Interval=1HOUR
Mapping Interval=1HOUR
Run HTab= 0
Run UNet= 0
Run Sediment= 0
Run PostProcess= 0
Run WQNet= 0
Run RASMapper= 0
UNET Theta= 1
UNET Theta Warmup= 1
UNET ZTol= 0.006
UNET ZSATol= 0.006
UNET MxIter= 20
UNET Max Iter WO Improvement= 0
UNET MaxInSteps= 0
UNET DtIC= 0
UNET DtMin= 0
UNET MaxCRTS= 20
UNET WFStab= 2
UNET SFStab= 1
UNET WFX= 1
UNET SFX= 1
UNET DSS MLevel= 4
UNET Pardiso=0
UNET DZMax Abort= 30
UNET Use Existing IB Tables=-1
UNET Froude Reduction=False
UNET Froude Limit= 0.8
UNET Froude Power= 4
UNET Time Slicing=0,0, 5
UNET D1 Cores= 0
UNET D2 Coriolis=0
UNET D2 Cores= 0
UNET D2 Theta= 1
UNET D2 Theta Warmup= 1
UNET D2 Z Tol= 0.003
UNET D2 Volume Tol= 0.003
UNET D2 Max Iterations= 20
UNET D2 Equation= 0
UNET D2 RampUpFraction=0.1
UNET D2 TimeSlices= 1
UNET D2 BCVolumeCheck=0
UNET D1D2 MaxIter= 0
UNET D1D2 ZTol=0.003
UNET D1D2 QTol=0.1
UNET D1D2 MinQTol=0.03
DSS File=dss
Write IC File= 0
Write IC File at Fixed DateTime=0
Write IC File at Sim End=0
Echo Input=False
Echo Parameters=False
Echo Output=False
Write Detailed= 0
HDF Write Warmup=0
HDF Write Time Slices=0
HDF Flush=0
HDF Face Node Velocities=0
HDF Compression= 1
HDF Chunk Size= 1
HDF Spatial Parts= 1
HDF Use Max Rows=0
HDF Fixed Rows= 1
Calibration Method= 0
Calibration Iterations= 20
Calibration Max Change=0.05
Calibration Tolerance=0.2
Calibration Maximum=1.5
Calibration Minimum=0.5
Calibration Optimization Method= 1
WQ AD Non Conservative
WQ ULTIMATE=-1
WQ Max Comp Step=1HOUR
WQ Output Interval=15MIN
WQ Output Selected Increments= 0
WQ Output face flow=0
WQ Output face velocity=0
WQ Output face area=0
WQ Output face dispersion=0
WQ Output cell volume=0
WQ Output cell surface area=0
WQ Output cell continuity=0
WQ Output cumulative cell continuity=0
WQ Output face conc=0
WQ Output face dconc_dx=0
WQ Output face courant=0
WQ Output face peclet=0
WQ Output face adv mass=0
WQ Output face disp mass=0
WQ Output cell mass=0
WQ Output cell source sink temp=0
WQ Output nsm pathways=0
WQ Output nsm derived pathways=0
WQ Output MaxMinRange=-1
WQ Daily Max Min Mean=-1
WQ Daily Range=0
WQ Daily Time=0
WQ Create Restart=0
WQ Fixed Restart=0
WQ System Summary=0
WQ Write To DSS=0
WQ Use Fixed Temperature=0
Sorting and Armoring Iterations= 10
XS Update Threshold= 0.02
Bed Roughness Predictor= 0
Hydraulics Update Threshold= 0.02
Energy Slope Method= 1
Volume Change Method= 1
Sediment Retention Method= 0
XS Weighting Method= 0
Number of US Weighted Cross Sections= 1
Number of DS Weighted Cross Sections= 1
Upstream XS Weight=0
Main XS Weight=1
Downstream XS Weight=0
Number of DS XS's Weighted with US Boundary= 1
Upstream Boundary Weight= 1
Weight of XSs Associated with US Boundary= 0
Number of US XS's Weighted with DS Boundary= 1
Downstream Boundary Weight= 0.5
Weight of XSs Associated with DS Boundary= 0.5
Percentile Method= 0
Sediment Output Level= 4
Mass or Volume Output= 0
Output Increment Type= 1
Profile and TS Output Increment= 1
XS Output Flag= 0
XS Output Increment= 10
Write Gradation File= 0
Read Gradation Hotstart= 0
Write HDF5 File= 1
Write DSS Sediment File= 0
SV Curve= 0
Specific Gage Flag= 0

--- HECRAS_v2.p01 (plan) ---

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Plan Title=HECRAS_v2_NP100
Short Identifier=HECRAS_v2_NP100
Simulation Date=05MAR2016,00:15,08MAR2016,00:15
Geom File=g02
Flow File=u02
Output Interval=15MIN
Run HTab= 1
Run UNet= 1
Run PostProcess= 1
Run RASMapper= 1
Computation Level Output=True

--- HECRAS_v2.p03 (plan) ---

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Plan Title=HECRAS_v2_NP2.33
Short Identifier=HECRAS_v2_NP2.33
Simulation Date=05MAR2016,00:15,08MAR2016,00:15
Geom File=g02
Flow File=u01
Output Interval=15MIN
Run HTab= 1
Run UNet= 1
Run PostProcess= 1
Run RASMapper= 1
UNET D2 Z Tol= 0.03
UNET D2 Volume Tol= 0.03
UNET D1D2 ZTol=0.03
Computation Level Output=True

--- HECRAS_v2.p04 (plan) ---

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Plan Title=HECRAS_v2_PermanenteA
Short Identifier=HECRAS_v2_PermanenteA
Geom File=g01
Flow File=f01

--- HECRAS_v2.f02 (steady flow) ---

Flow Title=HECRAS_v2_Permanente
Program Version=5.03
Number of Profiles= 2
Profile Names=Tr=2.33yr,Tr=100yr
River Rch & RM=ARROYOELZORRO,ARRIBALAT1      ,10516.63
     130   522.1
River Rch & RM=ARROYOELZORRO,ABAJOLAT1       ,8885.184
   129.6   519.7
River Rch & RM=LATERAL1,LATERAL1        ,4571.366
      42   122.2
Boundary for River Rch & Prof#=ARROYOELZORRO,ARRIBALAT1      , 1
Up Type= 2
Dn Type= 0
Boundary for River Rch & Prof#=ARROYOELZORRO,ARRIBALAT1      , 2
Up Type= 2
Dn Type= 0
Boundary for River Rch & Prof#=ARROYOELZORRO,ABAJOLAT1       , 1
Up Type= 0
Dn Type= 3
Dn Slope=0.0008969
Boundary for River Rch & Prof#=ARROYOELZORRO,ABAJOLAT1       , 2
Up Type= 0
Dn Type= 3
Dn Slope=0.0008969
Boundary for River Rch & Prof#=LATERAL1,LATERAL1        , 1
Up Type= 2
Dn Type= 0
Boundary for River Rch & Prof#=LATERAL1,LATERAL1        , 2
Up Type= 2
Dn Type= 0
DSS Import GetInterval= 0
DSS Import GetPeak= 0
DSS Import FillOption= 0

--- HECRAS_v2.f01 (steady flow) ---

Flow Title=HECRAS_v2_PermanenteA
Program Version=5.03
Number of Profiles= 1
Profile Names=Tr=2.33yr
River Rch & RM=ARROYOELZORRO,ARRIBALAT1      ,10516.63
     130
River Rch & RM=ARROYOELZORRO,ARRIBALAT1      ,8885.184
   129.6
River Rch & RM=ARROYOELZORRO,ABAJOLAT1       ,8885.184
   129.6
River Rch & RM=LATERAL1,LATERAL1        ,4571.366
      42
Boundary for River Rch & Prof#=ARROYOELZORRO,ARRIBALAT1      , 1
Up Type= 2
Dn Type= 3
Dn Slope=0.0008969
Boundary for River Rch & Prof#=ARROYOELZORRO,ABAJOLAT1       , 1
Up Type= 0
Dn Type= 3
Dn Slope=0.0008969
Boundary for River Rch & Prof#=LATERAL1,LATERAL1        , 1
Up Type= 2
Dn Type= 0
DSS Import GetInterval= 0
DSS Import GetPeak= 0
DSS Import FillOption= 0

--- HECRAS_v2.u01 (unsteady flow) ---

Flow Title=Tr2.33yrNoPermanente
Program Version=5.03
Use Restart= 0
Boundary Location=ARROYOELZORRO   ,ARRIBALAT1      ,10516.63,        ,                ,                ,                ,
Interval=1MIN
Flow Hydrograph= 4321
       0       0       0       0       0       0       0       0       0       0
       0       0       0       0       0       0       0       0       0       0
       0       0       0       0       0       0       0       0       0       0
       0       0       0       0       0       0       0       0       0       0
       0       0       0       0       0       0      .1      .1      .1      .1
      .1      .1      .1      .1      .1      .1      .2      .2      .2      .2
      .2      .2      .3      .3      .3      .3      .4      .4      .4      .4
      .5      .5      .5      .6      .6      .6      .7      .7      .7      .8
      .8      .9      .9       1       1     1.1     1.1     1.2     1.2     1.3
     1.4     1.4     1.5     1.6     1.6     1.7     1.8     1.8     1.9       2
     2.1     2.1     2.2     2.3     2.4     2.5     2.6     2.7     2.7     2.8
     2.9       3     3.1     3.2     3.3     3.4     3.5     3.6     3.8     3.9
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Use DSS=False
Use Fixed Start Time=True
Fixed Start Date/Time=05MAR2016,00:15
Is Critical Boundary=False
Boundary Location=LATERAL1        ,LATERAL1        ,4571.366,        ,                ,                ,                ,
Interval=1MIN
Flow Hydrograph= 4321
       0       0       0       0       0       0       0       0       0       0
       0       0       0       0       0       0       0       0       0       0
       0       0       0       0       0       0       0       0       0       0
       0      .1      .1      .1      .1      .1      .1      .1      .1      .1
      .1      .2      .2      .2      .2      .2      .3      .3      .3      .3
      .3      .4      .4      .4      .5      .5      .5      .6      .6      .7
      .7      .7      .8      .8      .9      .9       1       1     1.1     1.1
     1.2     1.2     1.3     1.4     1.4     1.5     1.6     1.6     1.7     1.8
     1.9     1.9       2     2.1     2.2     2.3     2.4     2.4     2.5     2.6
     2.7     2.8     2.9       3     3.1     3.2     3.3     3.5     3.6     3.7
     3.8     3.9     4.1     4.2     4.3     4.4     4.6     4.7     4.8       5
     5.1     5.3     5.4     5.6     5.7     5.9     6.1     6.2     6.4     6.5
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Use DSS=False
Use Fixed Start Time=True
Fixed Start Date/Time=05MAR2016,00:15
Is Critical Boundary=False
Boundary Location=ARROYOELZORRO   ,ARRIBALAT1      ,3253.451,        ,                ,                ,                ,
Friction Slope=0.0008969

--- HECRAS_v2.u02 (unsteady flow) ---

Flow Title=Tr100yrNoPermanente
Program Version=5.03
Use Restart= 0
Boundary Location=ARROYOELZORRO   ,ARRIBALAT1      ,10516.63,        ,                ,                ,                ,
Interval=1MIN
Flow Hydrograph= 4321
       0       0       0       0       0       0       0       0       0       0
       0       0       0       0       0       0       0       0       0       0
       0       0       0       0      .1      .1      .1      .1      .1      .1
      .1      .2      .2      .2      .3      .3      .3      .4      .4      .5
      .5      .6      .6      .7      .7      .8      .9       1     1.1     1.1
     1.2     1.3     1.4     1.5     1.7     1.8     1.9       2     2.2     2.3
     2.5     2.6     2.8     2.9     3.1     3.3     3.5     3.7     3.9     4.1
     4.3     4.5     4.7       5     5.2     5.4     5.7       6     6.2     6.5
     6.8     7.1     7.4     7.7       8     8.3     8.6     8.9     9.2     9.6
     9.9    10.3    10.6      11    11.4    11.7    12.1    12.5    12.9    13.3
    13.7    14.1    14.5    14.9    15.3    15.8    16.2    16.7    17.1    17.6
      18    18.5    18.9    19.4    19.9    20.4    20.9    21.4    21.8    22.4
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Use DSS=False
Use Fixed Start Time=True
Fixed Start Date/Time=05MAR2016,00:15
Is Critical Boundary=False
Boundary Location=LATERAL1        ,LATERAL1        ,4571.366,        ,                ,                ,                ,
Interval=1MIN
Flow Hydrograph= 4321
       0       0       0       0       0       0       0       0       0       0
       0       0       0       0       0       0       0       0      .1      .1
      .1      .1      .1      .1      .2      .2      .2      .2      .3      .3
      .3      .4      .4      .5      .5      .6      .6      .7      .8      .8
      .9       1     1.1     1.2     1.2     1.3     1.4     1.5     1.7     1.8
     1.9       2     2.1     2.3     2.4     2.6     2.7     2.9       3     3.2
     3.4     3.5     3.7     3.9     4.1     4.3     4.5     4.7     4.9     5.1
     5.4     5.6     5.8     6.1     6.3     6.6     6.8     7.1     7.3     7.6
     7.9     8.2     8.5     8.8     9.1     9.4     9.7    10.1    10.4    10.7
    11.1    11.5    11.8    12.2    12.6      13    13.3    13.7    14.2    14.6
      15    15.4    15.9    16.3    16.8    17.2    17.7    18.2    18.7    19.2
    19.7    20.2    20.7    21.2    21.8    22.3    22.9    23.5      24    24.6
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Use DSS=False
Use Fixed Start Time=True
Fixed Start Date/Time=05MAR2016,00:15
Is Critical Boundary=False
Boundary Location=ARROYOELZORRO   ,ARRIBALAT1      ,3253.451,        ,                ,                ,                ,
Friction Slope=0.0008969

--- HECRAS_v2.g01 (geometry) ---

Geom Title=HECRAS_v2
Program Version=5.03

Junct Name=1
Junct Desc=, 0 , 0 ,-1 ,0
Up River,Reach=ARROYOELZORRO   ,ARRIBALAT1
Up River,Reach=LATERAL1        ,LATERAL1
Dn River,Reach=ARROYOELZORRO   ,ABAJOLAT1
Junc L&A=0,0
Junc L&A=0,0

River Reach=ARROYOELZORRO   ,ARRIBALAT1
Reach XY= 30
 1080707.43739681573339.58328046 1080687.75229681573349.74338046
 1080636.31719681573396.41598046 1080550.59209681573432.29348046
 1080519.15949681573427.53098046 1080513.44449681573418.64098046
 1080528.04949681573365.61838046 1080525.50949681573345.61588046
 1080519.47699681573340.21838046 1080492.17189681573342.12338046
 1080422.95679681573444.67608046 1080410.83599681573501.83888046
 1080390.19849681573530.94308046 1080370.09009681573533.85348046
 1080237.79819681573498.13468046 1080173.23969681573449.18668046
 1080139.53599681573378.93498046 1080113.45989681573351.93548046
 1080078.08469681573339.38428046 1079986.11219681573341.36988046
 1079950.64689681573323.70618046 1079927.60339681573291.47588046
 1079900.99139681573205.31048046 1079862.93129681573168.18948046
 1079817.72299681573160.90368046 1079670.79339681573191.55538046
 1079620.59699681573176.35688046 1079592.46909681573141.01768046
 1079561.49079681573047.14748046 1079528.51909681573013.86438046

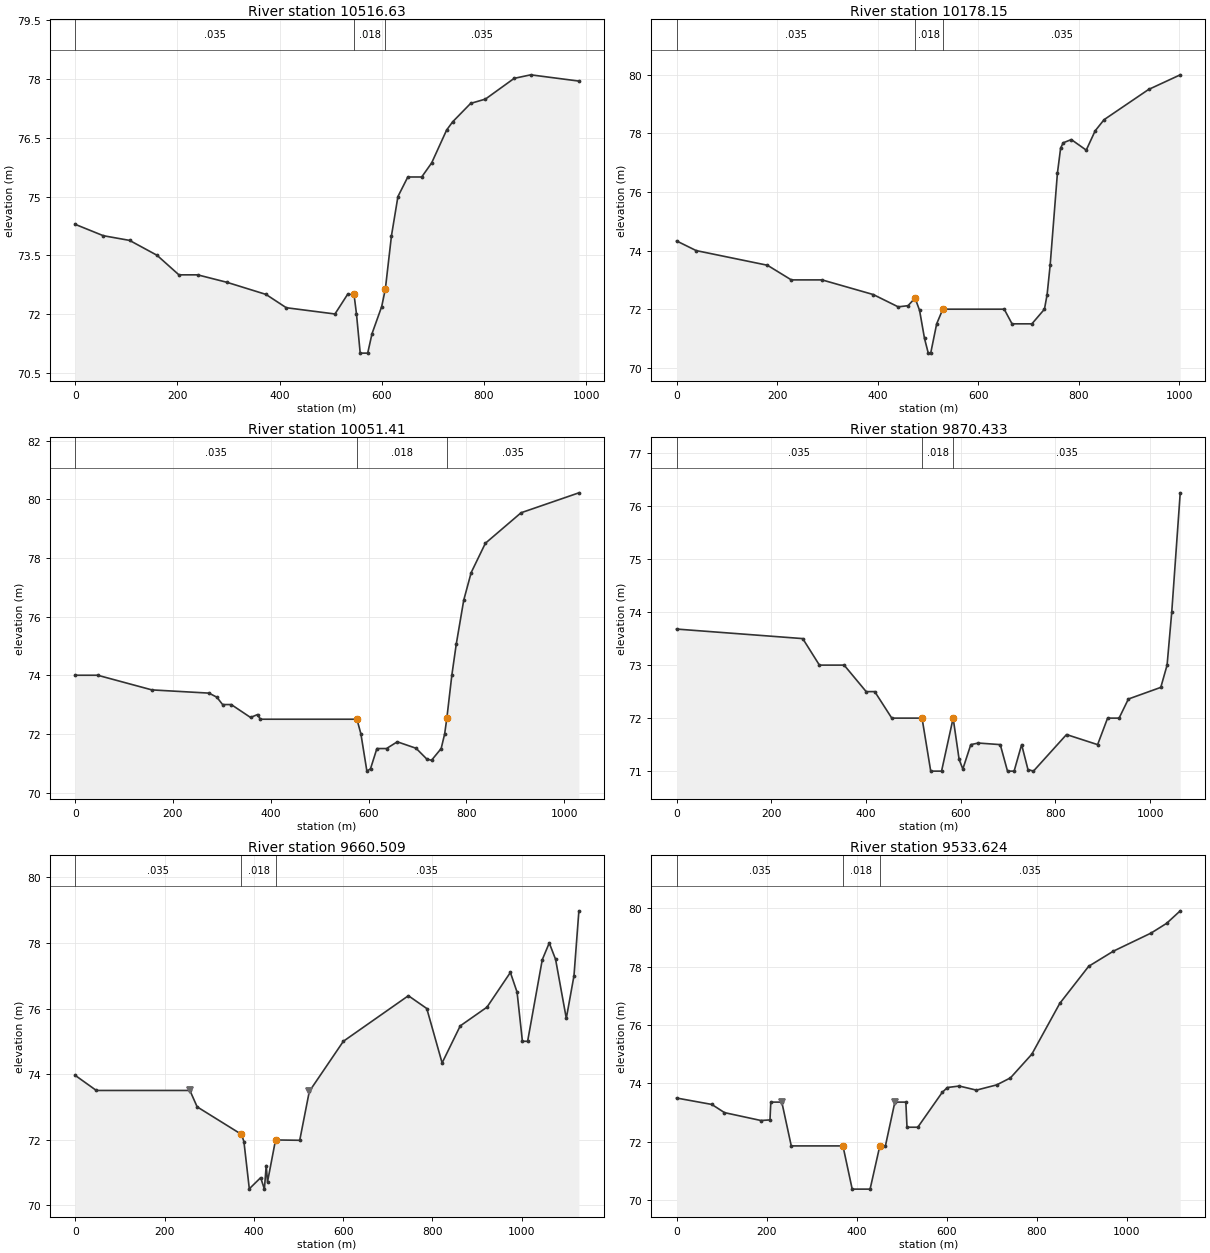
Type RM Length L Ch R = 1 ,10516.63,326.71,338.48,272.19
XS GIS Cut Line= 4
    1080327.0311    1572922.9204    1080508.3292    1573234.2431
    1080782.3396     1573544.788    1080904.0514    1573717.6348
#Sta/Elev= 30
       0   74.29   54.96      74  106.41   73.88  160.09    73.5  202.95      73
  239.59      73  296.77   72.81  373.39    72.5  413.09   72.16  508.37      72
  533.01    72.5  545.68    72.5   550.5      72  557.78      71  572.44      71
  580.98    71.5  599.85   72.19  607.03   72.64  618.98      74  631.62      75
  650.95    75.5  678.17    75.5  697.65   75.86  726.96    76.7  738.77   76.91
  773.94   77.38  802.87   77.49  859.15   78.02   891.6   78.11  985.81   77.95
#Mann= 3 , 0 , 0
       0    .035       0  545.68    .018       0  607.03    .035       0
Bank Sta=545.68,607.03
XS Rating Curve= 0 ,0
Exp/Cntr=0.3,0.1

Type RM Length L Ch R = 1 ,10178.15,130.71,126.74,122.71
XS GIS Cut Line= 4
    1080274.1143    1572941.9705    1080377.2263    1573318.1105
    1080566.5631    1573560.6676    1080749.9587    1573803.7037
#Sta/Elev= 30
       0   74.33   39.05      74  180.78    73.5  228.31      73  289.46      73
  391.35    72.5  440.96   72.08  460.63   72.12  474.55   72.38  483.53   71.96
  493.37      71  500.83    70.5  505.67    70.5  517.56    71.5  529.76      72
  651.94      72  667.53    71.5  707.05    71.5  732.02      72  737.33    72.5
  743.35    73.5  757.79   76.64  764.21    77.5  769.34   77.68  785.48   77.79
  815.14   77.43  832.97   78.09  850.74   78.47  939.19    79.5 1002.19      80
#Mann= 3 , 0 , 0
       0    .035       0  474.55    .018       0  529.76    .035       0
Bank Sta=474.55,529.76
XS Rating Curve= 0 ,0
Exp/Cntr=0.3,0.1

Type RM Length L Ch R = 1 ,10051.41,150.51,180.98,211.46
XS GIS Cut Line= 4
    1080240.2476    1572950.4372    1080352.9475    1573475.0008
     1080541.224    1573663.8071    1080671.8044    1573849.7252
#Sta/Elev= 30
       0      74   45.82      74  156.83    73.5  273.69   73.39   289.8   73.25
  301.48      73  319.19      73  358.67   72.56  373.11   72.66  378.61    72.5
  576.26    72.5  584.43      72  596.67   70.73  604.06   70.81  617.13    71.5
  636.79    71.5  658.87   71.73  697.24   71.51  719.35   71.14  728.91    71.1
  748.62    71.5  755.78      72  760.27   72.54  770.45      74  779.39   75.05
   794.8   76.56     810    77.5  839.05    78.5  912.04   79.54 1030.37   80.22
#Mann= 3 , 0 , 0
       0    .035       0  576.26    .018       0  760.27    .035       0
Bank Sta=576.26,760.27
XS Rating Curve= 0 ,0
Exp/Cntr=0.3,0.1

Type RM Length L Ch R = 1 ,9870.433,205.56,209.92,222.26
XS GIS Cut Line= 4
    1080202.1475    1572954.6705    1080254.1813     1573378.091
    1080194.4311    1573650.0588     1080377.746    1573958.0837
#Sta/Elev= 30
       0   73.68  266.43    73.5  301.61      73  353.82      73  400.36    72.5
  418.46    72.5  454.44      72  518.34      72  536.65      71  559.54      71
  584.02      72  596.64   71.22  604.48   71.04  621.28    71.5  637.17   71.53
   683.5    71.5  698.79      71  712.74      71  728.62    71.5  741.99   71.03
  753.58      71  823.39   71.69  889.07    71.5  910.13      72   934.4      72
  953.99   72.36 1022.46   72.58 1035.75      73 1045.59      74 1063.51   76.25
#Mann= 3 , 0 , 0
       0    .035       0  518.34    .018       0  584.02    .035       0
Bank Sta=518.34,584.02
XS Rating Curve= 0 ,0
Exp/Cntr=0.3,0.1

Type RM Length L Ch R = 1 ,9660.509,133.24,126.88,116.59
XS GIS Cut Line= 5
    1080161.9306    1572958.9446    1080152.5873    1573251.4818
    1080095.9811    1573338.1023    1079991.8435    1573479.1967
    1080234.5059    1573980.1218
#Sta/Elev= 30
       0   73.96   47.29    73.5  256.84    73.5  273.09      73  372.39   72.16
  377.86   71.94  389.93    70.5  415.39   70.84   423.7   70.49  427.79   71.21
  430.69   70.71  448.67   71.99  502.86   71.98  524.29   73.47  600.56      75
  746.21   76.39  787.41      76  821.77   74.34  862.37   75.47  922.19   76.04
  974.68    77.1  989.65    76.5 1001.61      75 1013.29      75 1046.13   77.49
 1061.74      78 1075.93    77.5 1099.93    75.7 1117.14      77 1128.13   78.98
#Mann= 3 , 0 , 0
       0    .035       0  372.39    .018       0  448.67    .035       0
Levee=-1,256.84,73.5,-1,524.29,73.47035,,	451
Bank Sta=372.39,448.67
XS Rating Curve= 0 ,0
Exp/Cntr=0.3,0.1

Type RM Length L Ch R = 1 ,9533.624,62.94,98.04,133.14
XS GIS Cut Line= 5
    1080109.3166     1572950.726    1080050.9978    1573155.8972
     1079943.577     1573386.726    1079923.5675    1573427.4895
    1079827.7994    1574025.7831
#Sta/Elev= 30
       0    73.5   78.34   73.28   106.5      73  187.46   72.73  207.56   72.75
  209.43   73.36  233.88   73.36  254.88   71.86  369.71   71.86  390.29   70.38
  430.04   70.38  451.65   71.86  464.08   71.86  485.08   73.36  509.48   73.36
  512.06    72.5  536.06    72.5  590.18   73.69  601.72   73.86  628.31   73.91
   666.3   73.77  711.47   73.95  741.98   74.19  789.41      75  851.53   76.74
  915.75   78.01  970.82   78.53 1054.62   79.15 1088.83   79.48 1119.22   79.91
#Mann= 3 , 0 , 0
       0    .035       0  369.71    .018       0  451.65    .035       0
Levee=-1,233.88,73.36314,-1,485.08,73.36273,	452,	451
Bank Sta=369.71,451.65
XS Rating Curve= 0 ,0
Exp/Cntr=0.3,0.1

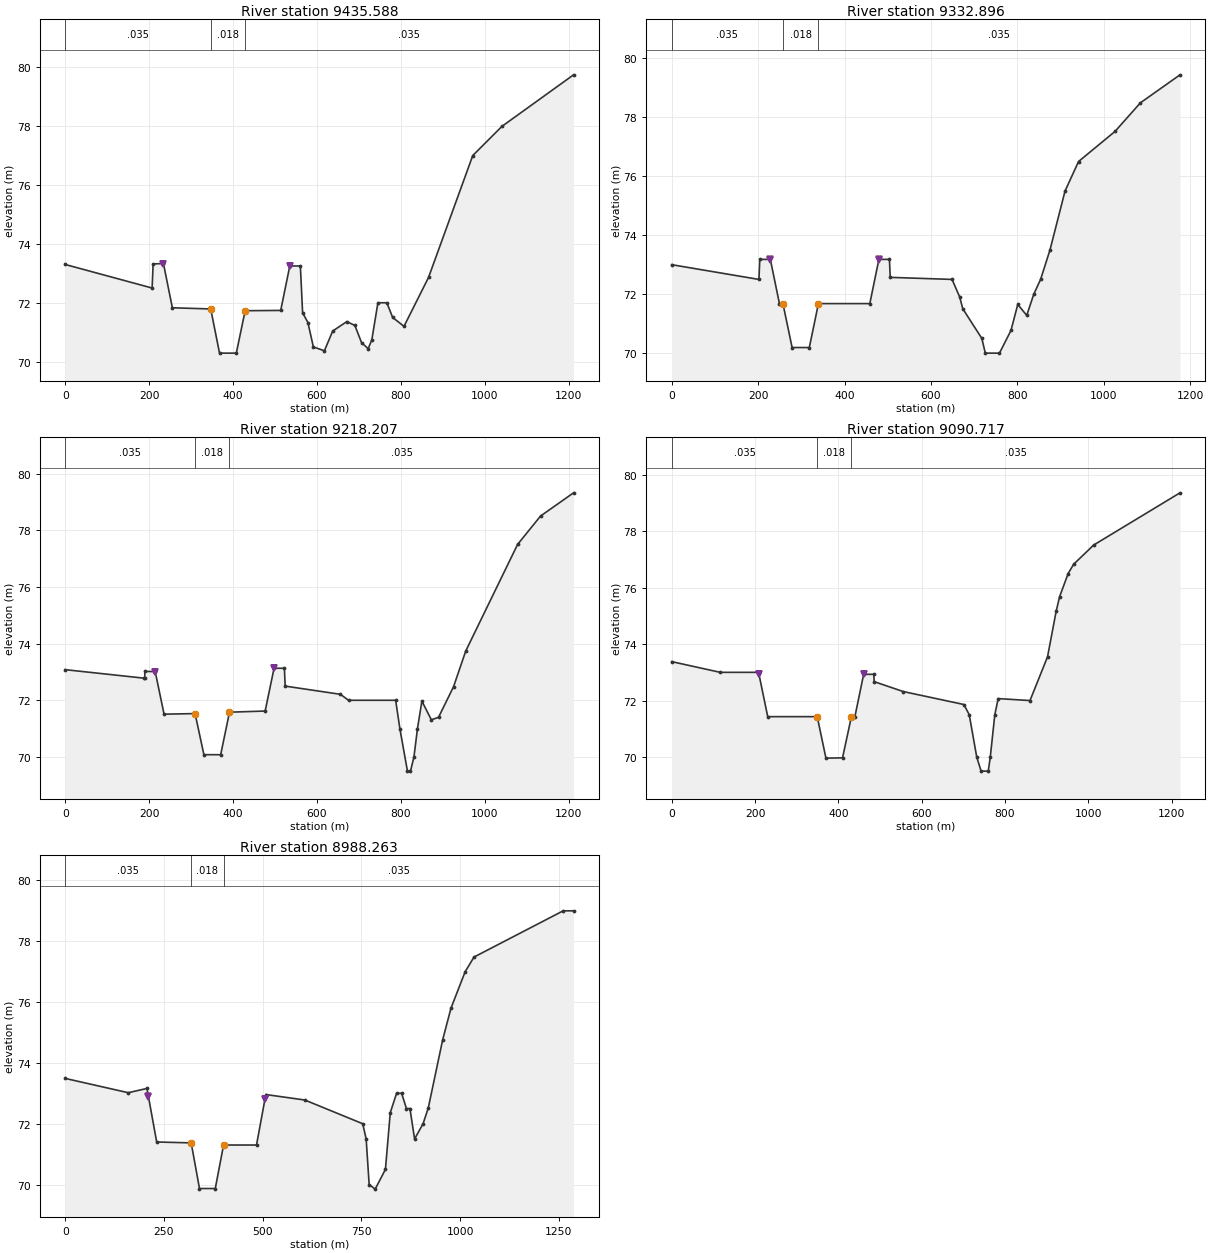
Type RM Length L Ch R = 1 ,9435.588,137.8,102.69,67.58
XS GIS Cut Line= 4
    1080083.4932    1572937.8142    1079991.2064    1573234.1482
     1079861.851     1573271.218    1079719.4258    1574024.0897
#Sta/Elev= 30
       0    73.3  207.07    72.5  209.48   73.32   234.1   73.33  255.29   71.83
   346.7   71.79   367.7   70.29   407.7   70.29   428.7   71.73  513.46   71.74
  535.12   73.25   560.3   73.25  565.65   71.66  578.22   71.33   591.3    70.5
   617.6   70.37  637.36   71.04  670.92   71.36  690.23   71.23  705.96   70.65
  721.87   70.44  730.54   70.74  745.07      72   766.4      72  780.24    71.5
  807.22    71.2  865.68   72.86  971.08      77 1040.58   77.99 1211.16   79.74
#Mann= 3 , 0 , 0
       0    .035       0   346.7    .018       0   428.7    .035       0
Levee=-1,234.1,73.32671,-1,535.13,73.24612,	452,	451
Bank Sta=346.7,428.7
XS Rating Curve= 0 ,0
Exp/Cntr=0.3,0.1

Type RM Length L Ch R = 1 ,9332.896,141.46,114.69,87.92
XS GIS Cut Line= 3
    1079992.4764    1572899.5025    1079778.3077     1573359.714
    1079621.0007    1574009.6964
#Sta/Elev= 30
       0      73  201.91    72.5  203.94   73.18  228.34   73.18  249.34   71.68
  257.43   71.68  278.72   70.19  318.56   70.19  339.62   71.68  458.54   71.68
  479.54   73.18  503.94   73.18  505.77   72.57  648.86    72.5  666.35   71.91
  673.85    71.5  717.72    70.5  725.81      70  758.58      70   785.2   70.77
  800.92   71.65  821.68   71.28  838.01      72  853.74    72.5  875.49    73.5
  910.34    75.5  941.61    76.5 1025.97   77.52 1084.68   78.49 1176.35   79.44
#Mann= 3 , 0 , 0
       0    .035       0  257.43    .018       0  339.62    .035       0
Levee=-1,228.34,73.17561,-1,479.54,73.17561,	452,	451
Bank Sta=257.43,339.62
XS Rating Curve= 0 ,0
Exp/Cntr=0.3,0.1

Type RM Length L Ch R = 1 ,9218.207,100.72,127.49,154.26
XS GIS Cut Line= 5
    1079875.0012    1572860.7674    1079739.5342    1573104.6079
    1079763.8079    1573214.4359    1079771.7076    1573257.0082
    1079542.2605    1573998.6897
#Sta/Elev= 30
       0   73.08  188.03   72.78  189.26   72.78  189.98   73.02  214.44   73.01
   235.5   71.51  309.42   71.53  330.42   70.08  370.42   70.08  391.42   71.58
  476.37   71.62  497.57   73.13  522.19   73.13  524.11    72.5  655.81   72.21
  674.96      72  787.28      72  797.42   70.99  815.42    69.5   822.6    69.5
  830.88      70  839.26      71  849.81   71.97  872.36   71.31  889.48    71.4
  925.24   72.48  954.33   73.74 1077.82    77.5 1132.44    78.5 1211.08   79.32
#Mann= 3 , 0 , 0
       0    .035       0  309.42    .018       0  391.42    .035       0
Levee=-1,214.44,73.01493,-1,497.56,73.12814,	452,	451
Bank Sta=309.42,391.42
XS Rating Curve= 0 ,0
Exp/Cntr=0.3,0.1

Type RM Length L Ch R = 1 ,9090.717,68.21,102.45,136.69
XS GIS Cut Line= 3
    1079795.4143     1572828.594    1079590.7473    1573268.3881
    1079386.4735    1573974.1363
#Sta/Elev= 30
       0   73.38  116.52      73  206.87      73  208.66   72.99  230.48   71.43
  349.22   71.43  370.18   69.96  410.01   69.97  431.31   71.43  439.68   71.43
  460.68   72.93  485.08   72.93   485.9   72.67  555.56   72.32  701.25   71.86
  714.03    71.5  732.03      70  742.52    69.5  759.73    69.5  764.57      70
  775.42    71.5  783.49   72.07  859.84      72  901.93   73.55  922.59   75.16
  930.92   75.68   951.4    76.5  964.59   76.83 1012.64   77.51  1219.8   79.36
#Mann= 3 , 0 , 0
       0    .035       0  349.22    .018       0  431.31    .035       0
Levee=-1,209.48,72.93304,-1,460.68,72.93301,	452,	451
Bank Sta=349.22,431.31
XS Rating Curve= 0 ,0
Exp/Cntr=0.3,0.1

Type RM Length L Ch R = 1 ,8988.263,137.11,103.08,68.73
XS GIS Cut Line= 4
    1079759.8543     1572810.814     1079645.554    1573077.6204
    1079521.3471    1573116.0751    1079286.2491    1573950.7471
#Sta/Elev= 30
       0   73.49  159.73   73.02  207.05   73.16  231.71    71.4  319.07   71.37
  340.07   69.87  380.07   69.87  401.07    71.3  484.52    71.3  508.09   72.96
  606.87   72.78   753.5      72  762.21    71.5  769.83      70  785.04   69.85
  811.06    70.5  823.24   72.36   839.2      73   852.1      73  864.25    72.5
   873.1    72.5  884.88    71.5  906.36      72  919.57   72.52     956   74.76
  977.07    75.8 1012.99      77  1035.4   77.48 1261.22      79 1287.43      79
#Mann= 3 , 0 , 0
       0    .035       0  319.07    .018       0  401.07    .035       0
Levee=-1,210.7,72.89437,-1,505.8,72.80102,	452,	451
Bank Sta=319.07,401.07
XS Rating Curve= 0 ,0
Exp/Cntr=0.3,0.1

River Reach=LATERAL1        ,LATERAL1
Reach XY= 30
 1081518.22889681570397.89268046 1081511.87889681570446.57608046
 1081461.92539681570477.90288046 1081153.94979681570449.53948046
 1081055.52459681570500.33958046 1081080.92469681570687.02988046
 1080962.81439681570866.10028046 1080974.87939681570928.96538046
 1081079.65469681571054.69568046 1081159.02979681571260.43608046
 1081169.18979681571352.51128046 1081112.67469681571549.99668046
 1081025.04449681571595.71678046 1080818.66909681571610.32178046
 1080738.02399681571650.32688046 1080469.41839681571690.96688046
 1080494.50099681571945.28498046 1080595.14869681572107.21028046
 1080410.68079681572306.91818046 1080314.16059681572330.73068046
 1080193.51039681572296.12318046 1080067.14509681572348.51078046
 1079951.89239681572216.74798046 1079907.75979681572209.76298046
 1079755.99449681572323.42818046 1079699.79689681572415.50338046
 1079697.25689681572607.90878046 1079609.62669681572706.01648046
 1079550.57159681572842.85928046       1079528.5     1573013.875

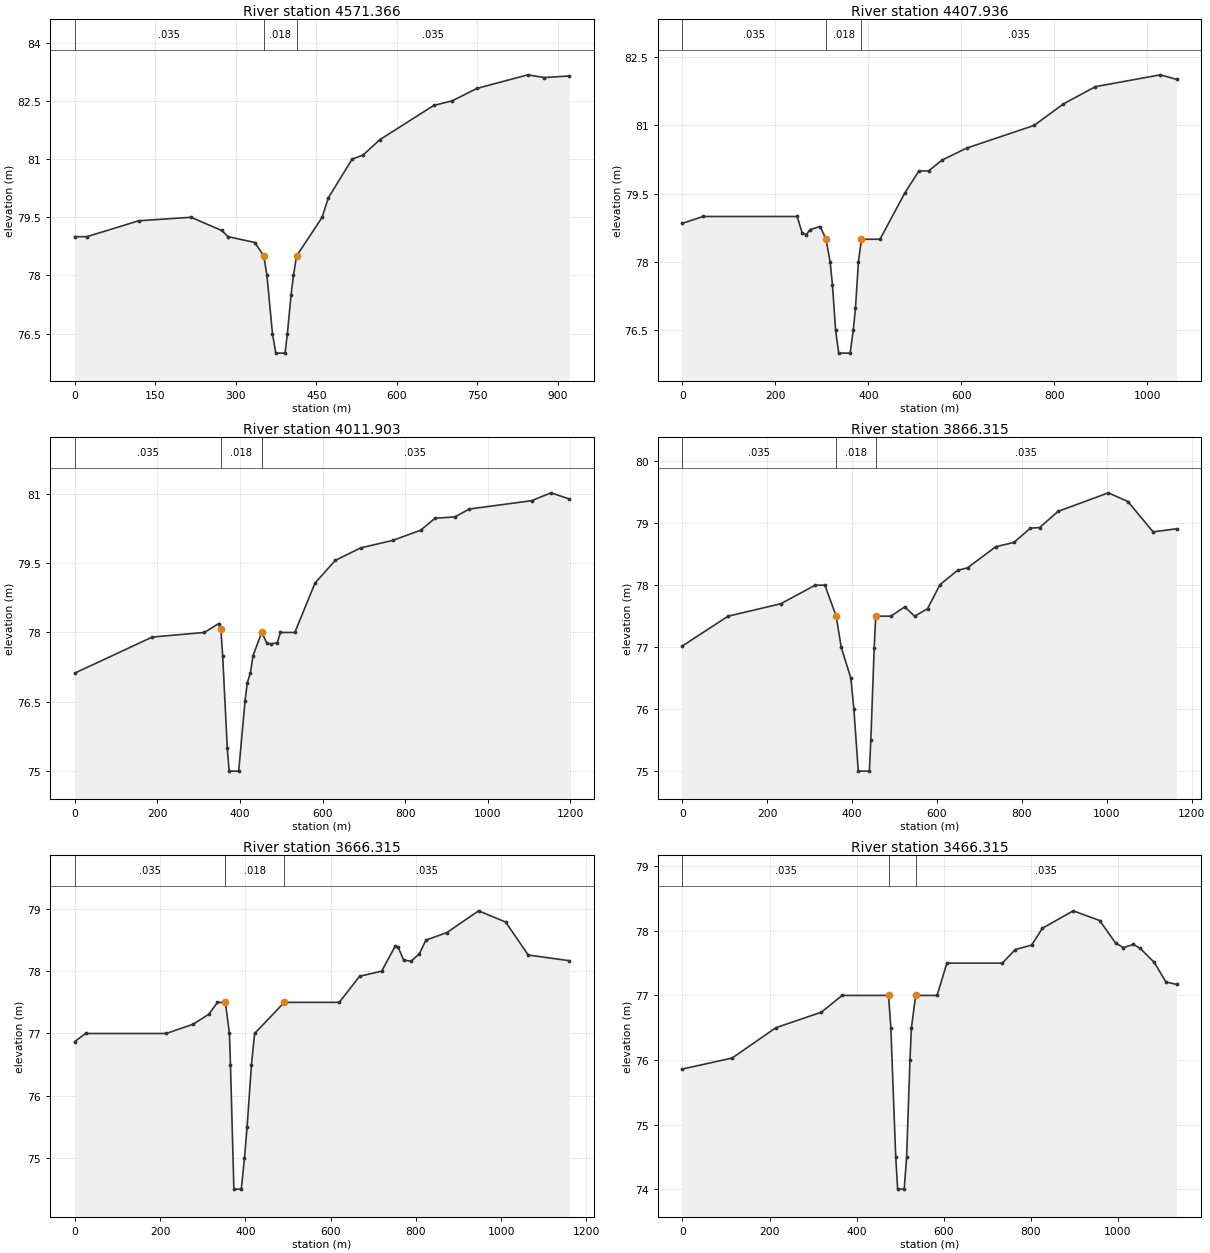
Type RM Length L Ch R = 1 ,4571.366,152.41,163.43,174.48
XS GIS Cut Line= 4
    1081393.6367    1570101.9591     1081441.199    1570332.9487
    1081520.5742    1570623.9909    1081860.0449    1570801.3279
#Sta/Elev= 27
       0      79   22.59      79  119.12   79.41  216.56    79.5  273.55   79.16
  285.76      79  335.51   78.85  352.15    78.5  357.99      78   368.3    76.5
  374.48      76   391.7      76  396.05    76.5  402.91    77.5  407.38      78
  413.09    78.5  460.85    79.5   472.3      80  516.74      81  536.76    81.1
  568.36    81.5  668.54   82.38  703.02    82.5  749.23   82.82  843.89   83.17
   874.3    83.1  920.51   83.14
#Mann= 3 , 0 , 0
       0    .035       0  352.15    .018       0  413.09    .035       0
Bank Sta=352.15,413.09
XS Rating Curve= 0 ,0
Exp/Cntr=0.3,0.1

Type RM Length L Ch R = 1 ,4407.936,443.54,396.03,348.49
XS GIS Cut Line= 4
    1081253.6858     1570142.195    1081335.3655    1570306.4903
    1081306.8387     1570585.175    1081790.6318    1570939.9528
#Sta/Elev= 28
       0   78.85   44.52      79  246.94      79  257.64   78.64  266.41    78.6
  274.62   78.71  296.55   78.78  309.08    78.5  317.91      78  322.92    77.5
  329.69    76.5  336.34      76  360.94      76  367.69    76.5  372.39   76.98
  378.77      78  385.27    78.5  425.28    78.5   478.3   79.51  508.98      80
  529.77      80  559.12   80.24   611.4    80.5  756.96      81  819.72   81.47
  888.71   81.85 1028.57   82.11 1063.56   82.01
#Mann= 3 , 0 , 0
       0    .035       0  309.08    .018       0  385.27    .035       0
Bank Sta=309.08,385.27
XS Rating Curve= 0 ,0
Exp/Cntr=0.3,0.1

Type RM Length L Ch R = 1 ,4011.903,127.44,145.59,163.74
XS GIS Cut Line= 4
    1080708.7383    1570491.5304    1080921.5307    1570597.1121
    1081192.4902    1570621.3451    1081748.8517    1571024.5408
#Sta/Elev= 30
       0   77.12  187.64    77.9  314.07      78  348.21   78.19  353.85   78.07
  358.17    77.5  369.27   75.51   373.9      75     397      75  412.29   76.51
  417.77   76.91  425.44   77.13  431.74    77.5  452.77      78  464.98   77.77
  475.06   77.75  490.37   77.78  498.14      78  532.95      78  581.92   79.07
  631.16   79.56  692.61   79.83  769.64   79.99  837.48   80.21  872.46   80.47
  920.67    80.5  955.68   80.67 1106.34   80.85 1153.18   81.02 1196.69   80.89
#Mann= 3 , 0 , 0
       0    .035       0  353.85    .018       0  452.77    .035       0
Bank Sta=353.85,452.77
XS Rating Curve= 0 ,0
Exp/Cntr=0.3,0.1

Type RM Length L Ch R = 1 ,3866.315,225.37,200,174.75
XS GIS Cut Line= 4
    1080660.7755    1570590.9984    1080958.4221    1570667.3234
    1081175.4436    1570853.3408    1081659.8275    1571156.3035
#Sta/Elev= 30
       0   77.02  107.61    77.5  231.58    77.7  312.95      78  335.73      78
  362.24    77.5  374.15      77  396.85    76.5  403.98      76  414.38      75
  440.59      75  443.95    75.5  451.88   76.99  455.46    77.5  491.12    77.5
  523.92   77.65  547.09    77.5  577.54   77.62  606.89   78.01   648.6   78.24
   671.8   78.28  738.23   78.62  781.16   78.69  819.96   78.92  841.68   78.93
  884.91   79.19  1003.6   79.49 1049.65   79.35 1109.03   78.86 1164.44   78.91
#Mann= 3 , 0 , 0
       0    .035       0  362.24    .018       0  455.46    .035       0
Bank Sta=362.24,455.46
XS Rating Curve= 0 ,0
Exp/Cntr=0.3,0.1

Type RM Length L Ch R = 1 ,3666.315,208.53,200,191.35
XS GIS Cut Line= 4
    1080591.5109    1570888.9546    1080787.6296    1570935.8453
     1081141.525    1570888.6593    1081641.6243    1571220.7033
#Sta/Elev= 30
       0   76.87   25.29      77  214.53      77  278.02   77.15  314.66   77.31
  334.66    77.5  353.25    77.5  362.73      77  365.18    76.5  373.23    74.5
  390.54    74.5  398.08      75  404.18    75.5   414.4    76.5  421.85      77
  491.43    77.5  620.24    77.5  668.23   77.92  719.59      78  751.34    78.4
  758.02   78.39  771.37   78.18  788.64   78.16  808.24   78.28   823.6    78.5
  872.58   78.62  947.16   78.97 1010.47   78.79 1063.58   78.26 1158.97   78.17
#Mann= 3 , 0 , 0
       0    .035       0  353.25    .018       0  491.43    .035       0
Bank Sta=353.25,491.43
XS Rating Curve= 0 ,0
Exp/Cntr=0.3,0.1

Type RM Length L Ch R = 1 ,3466.315,196.37,200,203.63
XS GIS Cut Line= 4
     1080606.752    1571080.9971    1080921.7505    1571143.2625
    1081221.8512    1571010.8655    1081624.2068    1571282.5043
#Sta/Elev= 29
       0   75.86   114.1   76.03  214.64    76.5  319.04   76.74  366.74      77
  473.26      77  478.48    76.5   489.7    74.5  494.18      74  509.17      74
  514.75    74.5  522.46      76  525.79    76.5  535.57      77  584.65      77
  607.19    77.5  734.46    77.5  764.18   77.71  801.81   77.78  826.41   78.04
  897.13   78.31  957.89   78.16  994.72   77.81  1012.4   77.74 1035.17   77.79
 1050.79   77.73 1083.44   77.51 1109.79   77.21 1134.57   77.17
#Mann= 3 , 0 , 0
       0    .035       0  473.26    .018       0  535.57    .035       0
Bank Sta=473.26,535.57
XS Rating Curve= 0 ,0
Exp/Cntr=0.3,0.1

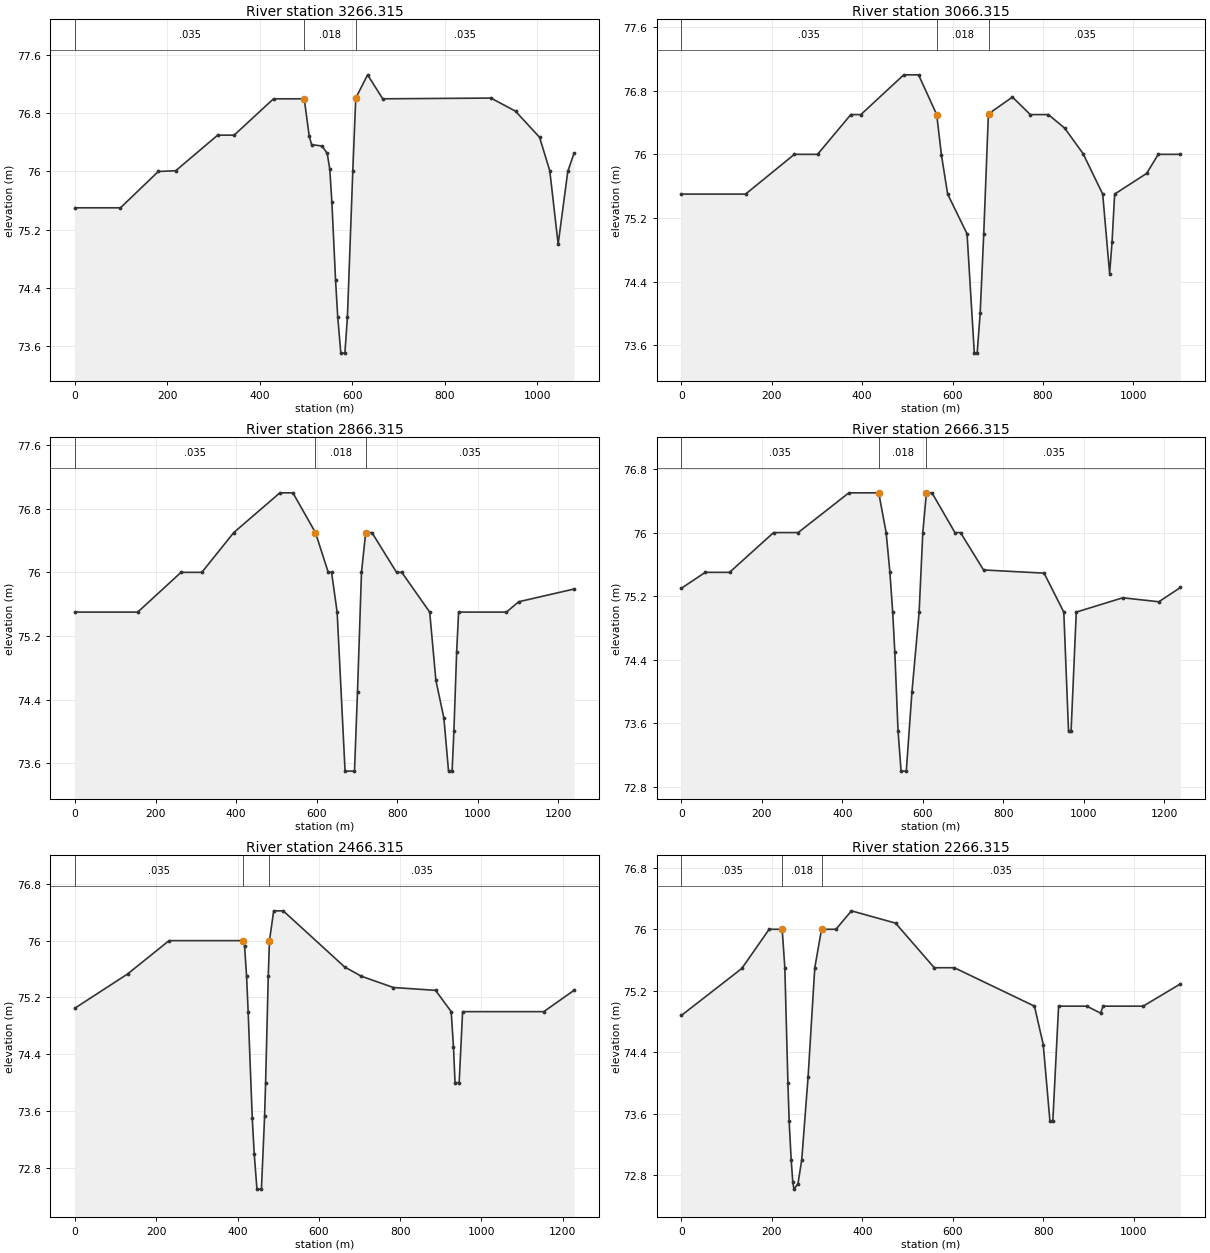
Type RM Length L Ch R = 1 ,3266.315,184.79,200,215.21
XS GIS Cut Line= 4
    1080595.0101    1571256.4086    1080957.9986    1571317.8097
    1081316.1518    1571209.0849    1081593.8293    1571399.4434
#Sta/Elev= 30
       0    75.5   98.33    75.5  180.22      76  217.81   76.01  308.54    76.5
  344.18    76.5  429.31      77  495.72      77  506.44   76.49  511.56   76.37
  534.21   76.35   545.4   76.25  551.03   76.03  555.49   75.58  563.52    74.5
  568.16      74  574.91    73.5  583.66    73.5  589.15      74  600.69      76
  607.17   77.01  632.77   77.33  665.46      77  899.52   77.01   952.6   76.83
 1004.65   76.47 1026.74   76.01 1044.84      75 1065.64      76  1079.1   76.25
#Mann= 3 , 0 , 0
       0    .035       0  495.72    .018       0  607.17    .035       0
Bank Sta=495.72,607.17
XS Rating Curve= 0 ,0
Exp/Cntr=0.3,0.1

Type RM Length L Ch R = 1 ,3066.315,165.67,200,234.33
XS GIS Cut Line= 4
    1080510.4142    1571327.4268    1080932.1897    1571407.2786
    1081343.4433    1571495.4044    1081546.3129    1571648.9608
#Sta/Elev= 30
       0    75.5  141.84    75.5  249.87      76  301.21      76  374.81    76.5
     397    76.5  491.95      77  524.68      77  564.84    76.5  575.39   75.99
  589.07    75.5  632.03      75   648.1    73.5  654.41    73.5  661.02      74
  668.93      75   679.2    76.5  679.78   76.51  732.44   76.72  771.91    76.5
  811.96    76.5  848.02   76.33  888.68   76.01  932.18    75.5  947.53    74.5
  952.92    74.9  958.64    75.5 1029.37   75.76 1055.21      76 1104.29      76
#Mann= 3 , 0 , 0
       0    .035       0  564.84    .018       0  679.78    .035       0
Bank Sta=564.84,679.78
XS Rating Curve= 0 ,0
Exp/Cntr=0.3,0.1

Type RM Length L Ch R = 1 ,2866.315,192.19,200,207.81
XS GIS Cut Line= 4
    1080480.4185    1571356.0345    1080998.9119    1571452.4209
    1081074.7051    1571789.2748    1081372.5527    1572002.1389
#Sta/Elev= 30
       0    75.5  155.77    75.5  263.17      76  314.87      76  394.08    76.5
  508.65      77  540.95      77  596.91    76.5   628.7      76  636.94      76
  650.75    75.5  670.45    73.5  693.83    73.5  701.31    74.5  711.22      76
  721.63    76.5  737.08    76.5  798.23      76  811.26      76   880.5    75.5
  895.95   74.64   915.7   74.17   927.3    73.5  936.17    73.5  940.58      74
  947.45      75  952.29    75.5 1071.15    75.5 1101.27   75.63 1238.74   75.79
#Mann= 3 , 0 , 0
       0    .035       0  596.91    .018       0  721.63    .035       0
Bank Sta=596.91,721.63
XS Rating Curve= 0 ,0
Exp/Cntr=0.3,0.1

Type RM Length L Ch R = 1 ,2666.315,198.69,200,201.31
XS GIS Cut Line= 4
    1080413.8089    1571417.1216    1080837.3071    1571491.9031
     1080825.417    1571801.0496    1081227.9039    1572100.2957
#Sta/Elev= 30
       0    75.3   59.16    75.5   119.6    75.5  229.11      76  290.18      76
  416.36    76.5  490.59    76.5  509.01      76  518.39    75.5   525.3      75
  530.54    74.5  538.59   73.51  546.13      73  559.12      73  573.11   73.99
  591.05      75  600.21      76  609.19    76.5  623.05    76.5  680.09      76
  693.95      76  751.24   75.53  901.81   75.49  950.83      75  962.64    73.5
  968.92    73.5  981.86      75 1097.49   75.18 1187.19   75.13 1240.97   75.31
#Mann= 3 , 0 , 0
       0    .035       0  490.59    .018       0  609.19    .035       0
Bank Sta=490.59,609.19
XS Rating Curve= 0 ,0
Exp/Cntr=0.3,0.1

Type RM Length L Ch R = 1 ,2466.315,249.51,200,150.31
XS GIS Cut Line= 4
    1080356.2232    1571464.6942    1080655.8705    1571508.8005
    1080636.4999    1571737.3738    1081190.6132    1572157.6623
#Sta/Elev= 28
       0   75.05  129.25   75.53  231.45      76  414.03      76  417.14   75.93
  422.16    75.5  426.04      75  436.16    73.5  440.94      73  447.68    72.5
   458.7    72.5  466.52   73.53  468.97      74  475.54    75.5  478.49      76
  488.87   76.42   512.3   76.42  663.32   75.63  704.07    75.5  783.39   75.34
  887.13    75.3   925.6      75  931.26    74.5  935.05      74   945.2      74
  953.65      75 1153.43      75 1227.74    75.3
#Mann= 3 , 0 , 0
       0    .035       0  414.03    .018       0  478.49    .035       0
Bank Sta=414.03,478.49
XS Rating Curve= 0 ,0
Exp/Cntr=0.3,0.1

Type RM Length L Ch R = 1 ,2266.315,208.24,200,191.76
XS GIS Cut Line= 4
    1080212.2983    1571692.6391    1080255.2301    1571702.1731
    1080547.5626    1571712.6135     1081148.028    1572190.0326
#Sta/Elev= 30
       0   74.88  133.44   75.49  193.89      76  222.74      76  228.63    75.5
  235.47      74  238.21    73.5  242.68      73  246.26   72.71  248.74   72.62
  257.67   72.69     266      73  280.08   74.08  294.88    75.5  309.83      76
  341.67      76  375.91   76.24  473.47   76.08  559.14    75.5  603.46    75.5
  780.73      75  800.12    74.5  815.02    73.5  821.27    73.5  834.08      75
  896.57      75  926.78   74.91  932.61      75 1021.16      75 1103.63   75.29
#Mann= 3 , 0 , 0
       0    .035       0  222.74    .018       0  309.83    .035       0
Bank Sta=222.74,309.83
XS Rating Curve= 0 ,0
Exp/Cntr=0.3,0.1