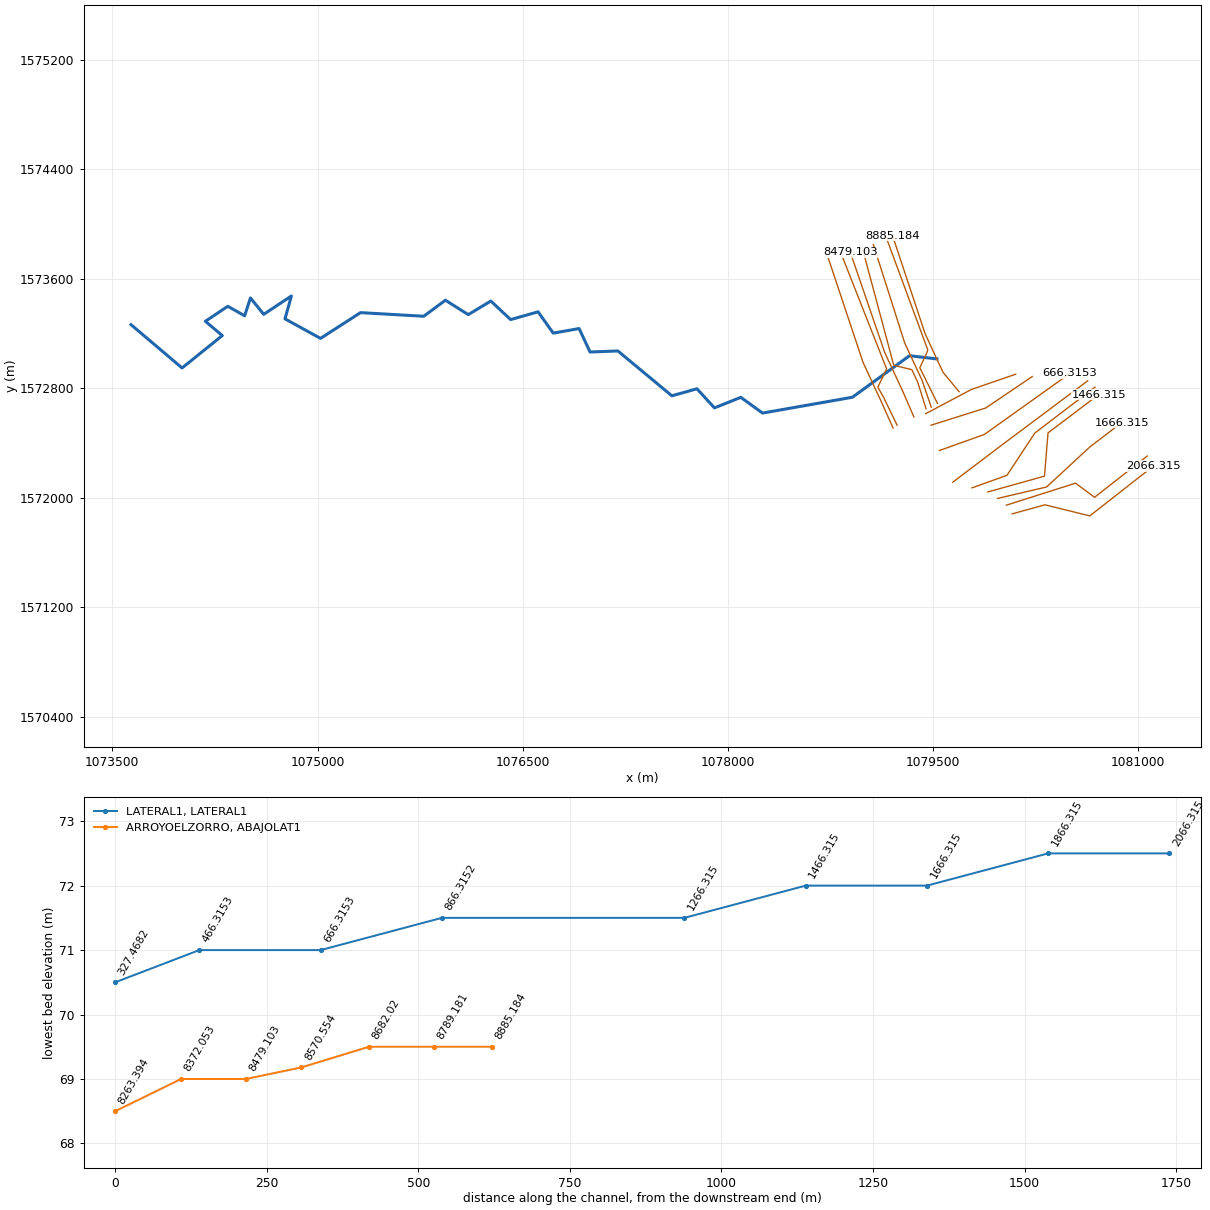
HEC-RAS study HECRAS_v2.prj: HECRAS_v2

--- HECRAS_v2.g01 (geometry) --- (continued)

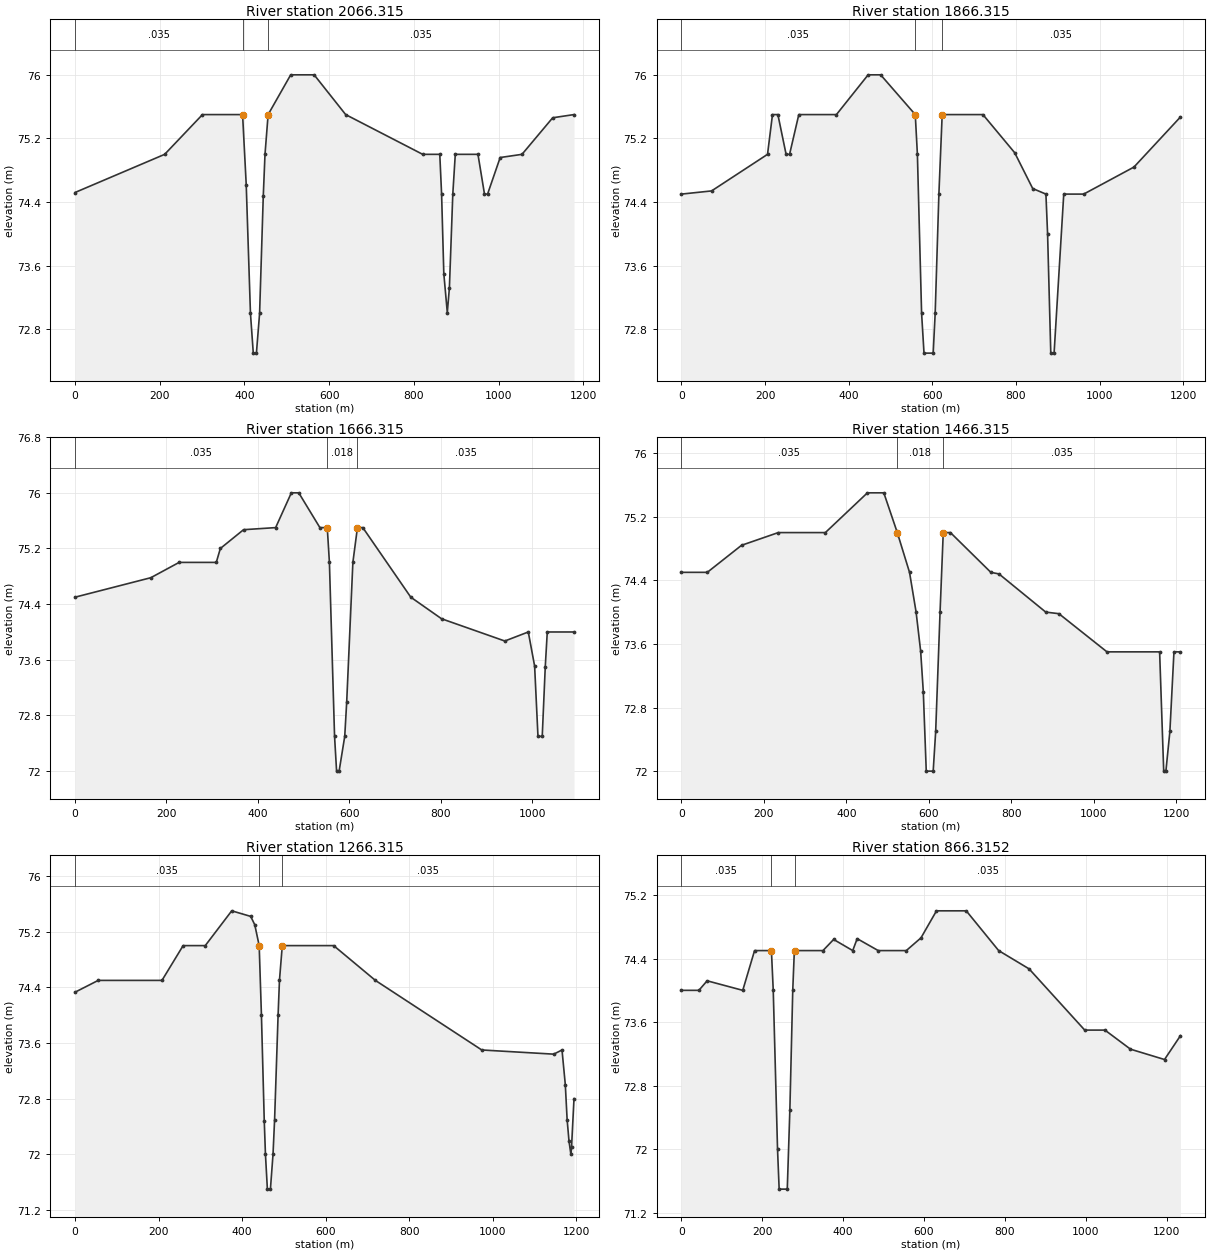
Type RM Length L Ch R = 1 ,2066.315,211.93,200,188.07
XS GIS Cut Line= 4
    1080078.1307    1571881.4182    1080317.4153     1571947.621
    1080645.3778    1571866.6952    1081111.3766    1572231.5927
#Sta/Elev= 30
       0   74.52   211.7      75  300.93    75.5  395.62    75.5  404.18   74.62
   414.2      73  420.87    72.5  428.26    72.5  435.78      73  444.41   74.47
  448.53      75   455.9    75.5   509.2      76  564.57      76  638.95    75.5
   820.8      75  861.11      75  865.39    74.5  870.63    73.5  878.86   73.01
   883.8   73.32  891.84    74.5   897.7      75  951.24      75  966.65    74.5
  973.92    74.5 1003.67   74.96 1055.17      75 1127.66   75.46 1177.94    75.5
#Mann= 3 , 0 , 0
       0    .035       0  395.62    .018       0   455.9    .035       0
Bank Sta=395.62,455.9
XS Rating Curve= 0 ,0
Exp/Cntr=0.3,0.1

Type RM Length L Ch R = 1 ,1866.315,158.12,200,241.88
XS GIS Cut Line= 4
    1080035.6115    1571945.0255    1080541.2594    1572105.8958
    1080680.2679    1572002.6317    1081065.8008    1572304.3412
#Sta/Elev= 30
       0    74.5   72.07   74.54  205.82      75  217.69    75.5   230.6    75.5
  250.24      75  258.55      75  280.63    75.5  370.62    75.5  446.42      76
  476.36      76  559.14    75.5  564.22      75  574.28      73  580.04    72.5
  601.97    72.5  606.75      73  615.63    74.5  623.49    75.5  720.93    75.5
  796.96   75.02  839.99   74.57  871.58    74.5  875.56      74  883.22    72.5
  891.13    72.5  914.23    74.5  961.95    74.5 1082.12   74.84 1193.34   75.47
#Mann= 3 , 0 , 0
       0    .035       0  559.14    .018       0  623.49    .035       0
Bank Sta=559.14,623.49
XS Rating Curve= 0 ,0
Exp/Cntr=0.3,0.1

Type RM Length L Ch R = 1 ,1666.315,177.66,200,222.34
XS GIS Cut Line= 4
    1079970.6561    1571994.2082    1080329.7154    1572077.9904
    1080643.9976    1572369.1636    1080877.7629    1572548.1553
#Sta/Elev= 30
       0    74.5  165.85   74.78  227.76      75  309.06      75  317.96    75.2
   368.7   75.47  438.91    75.5  473.27      76  489.48      76  535.71    75.5
  551.85    75.5  556.53      75   567.8    72.5  572.23      72  577.77      72
  590.06    72.5   594.4      73  607.86      75  617.83    75.5  629.63    75.5
  734.54    74.5  801.84   74.19  940.24   73.87  991.57      74 1005.43   73.51
 1012.74    72.5 1022.07    72.5 1028.71    73.5  1033.1      74 1091.56      74
#Mann= 3 , 0 , 0
       0    .035       0  551.85    .018       0  617.83    .035       0
Bank Sta=551.85,617.83
XS Rating Curve= 0 ,0
Exp/Cntr=0.3,0.1

Type RM Length L Ch R = 1 ,1466.315,215.04,200,184.95
XS GIS Cut Line= 4
    1079900.4549     1572041.573    1080314.2202    1572157.3594
    1080340.1248     1572473.396    1080710.0367    1572753.1583
#Sta/Elev= 29
       0    74.5   62.68    74.5  145.72   74.84   234.9      75  349.11      75
  451.14    75.5   490.9    75.5   523.6      75  553.27    74.5  569.22      74
  580.24   73.51  586.69      73  593.86      72  610.69      72  616.73    72.5
  627.34      74  635.08      75  652.52      75  750.56    74.5  770.29   74.48
  883.71      74  915.67   73.98 1032.25    73.5 1159.98    73.5  1169.9      72
 1175.22      72 1184.89    72.5 1194.77    73.5 1210.55    73.5
#Mann= 3 , 0 , 0
       0    .035       0   523.6    .018       0  635.08    .035       0
Bank Sta=523.6,635.08
XS Rating Curve= 0 ,0
Exp/Cntr=0.3,0.1

Type RM Length L Ch R = 1 ,1266.315,410.51,400,389.53
XS GIS Cut Line= 4
    1079784.3397     1572071.356    1080040.1108    1572163.4889
    1080243.6466    1572472.3018    1080683.0551    1572807.7735
#Sta/Elev= 30
       0   74.33   55.54    74.5   208.2    74.5  258.86      75  311.83      75
  375.22    75.5  420.61   75.42  430.34    75.3  440.92      75  446.31      74
  453.08   72.48  455.92      72  460.55    71.5  467.82    71.5  474.04      72
  477.82    72.5  486.19      74  489.47    74.5  496.21      75   619.2      75
  719.12    74.5  973.75    73.5 1146.08   73.44 1165.84    73.5 1173.76      73
 1178.08    72.5 1182.58   72.19 1187.11      72 1188.63    72.1 1194.54    72.8
#Mann= 3 , 0 , 0
       0    .035       0  440.92    .018       0  496.21    .035       0
Bank Sta=440.92,496.21
XS Rating Curve= 0 ,0
Exp/Cntr=0.3,0.1

Type RM Length L Ch R = 1 ,866.3152,209.16,200,190.8
XS GIS Cut Line= 3
    1079643.4541    1572112.7012    1080005.4348    1572386.9289
    1080630.2867    1572854.0753
#Sta/Elev= 30
       0      74   43.11      74   63.48   74.12  151.63      74  180.83    74.5
  222.51    74.5  227.04      74  237.66      72  241.66    71.5  261.73    71.5
  268.17    72.5  275.29      74  279.23    74.5     280    74.5  350.02    74.5
  376.43   74.64  423.64    74.5  434.65   74.65  486.71    74.5  556.13    74.5
  592.45   74.66  630.84      75  704.45      75  784.57    74.5   859.9   74.27
  997.48    73.5 1047.47    73.5 1110.69   73.26 1194.83   73.13  1234.3   73.43
#Mann= 3 , 0 , 0
       0    .035       0  222.51    .018       0     280    .035       0
Bank Sta=222.51,280
XS Rating Curve= 0 ,0
Exp/Cntr=0.3,0.1

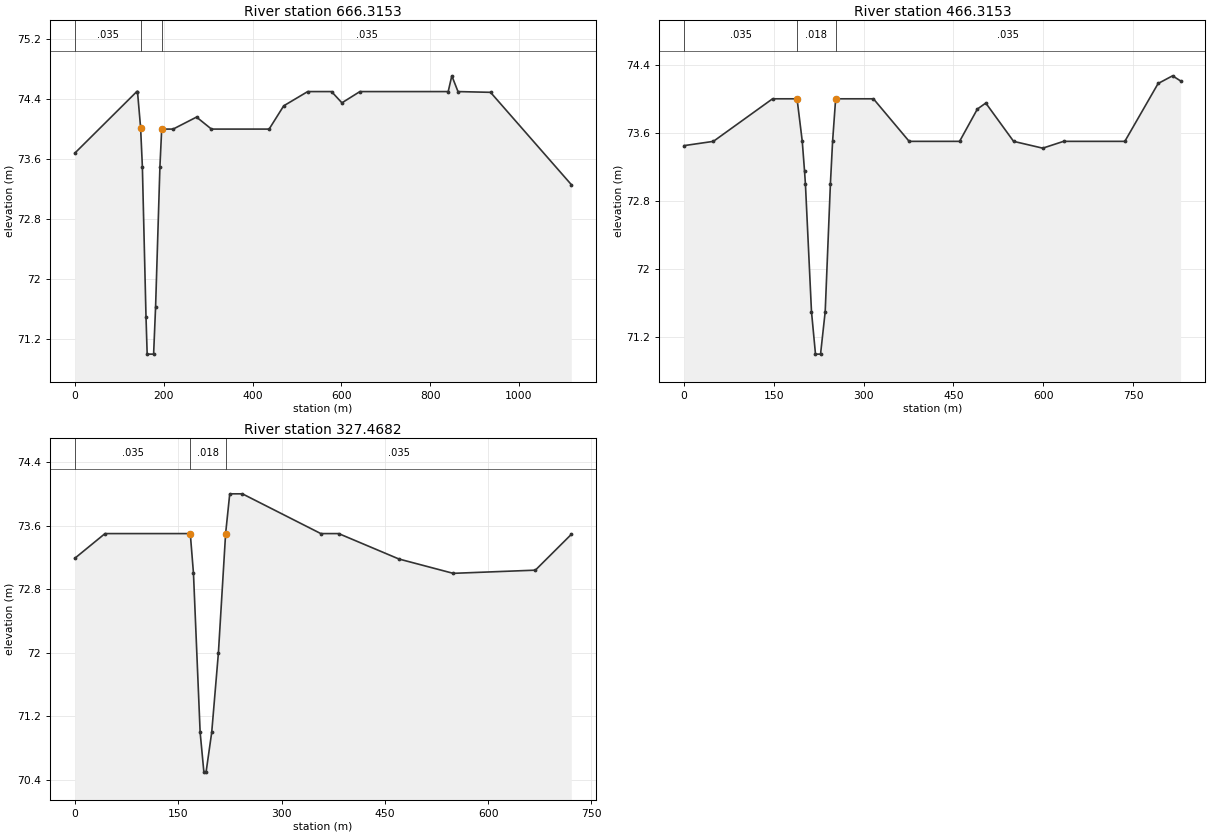
Type RM Length L Ch R = 1 ,666.3153,201.09,200,198.91
XS GIS Cut Line= 3
     1079545.912    1572344.5175     1079874.612    1572461.9099
    1080500.4923    1572908.3154
#Sta/Elev= 25
       0   73.68  139.44    74.5  141.01    74.5  148.02   74.02  151.99    73.5
  160.17    71.5  162.81      71  177.32      71  181.77   71.63  191.54    73.5
  195.51      74  221.24      74  273.97   74.16  307.56      74   437.4      74
  470.25   74.31  524.23    74.5   577.9    74.5  601.32   74.35   641.8    74.5
  840.62    74.5  848.79   74.71  862.69    74.5  935.95   74.49  1117.8   73.26
#Mann= 3 , 0 , 0
       0    .035       0  148.02    .018       0  195.51    .035       0
Bank Sta=148.02,195.51
XS Rating Curve= 0 ,0
Exp/Cntr=0.3,0.1

Type RM Length L Ch R = 1 ,466.3153,133.35,138.85,144.35
XS GIS Cut Line= 3
    1079485.0302    1572529.6118     1079885.609      1572655.92
    1080224.8188    1572885.3892
#Sta/Elev= 26
       0   73.45   48.82    73.5  147.69      74  188.66      74  197.37    73.5
  201.16   73.15  202.63      73  212.77    71.5  219.46      71  227.92      71
  235.69    71.5  244.38      73  248.04    73.5  253.15      74  316.28      74
  376.01    73.5  460.25    73.5     490   73.88  504.04   73.95  550.52    73.5
  599.18   73.42  633.96    73.5  736.37    73.5  792.01   74.18  816.14   74.27
  829.56   74.21
#Mann= 3 , 0 , 0
       0    .035       0  188.66    .018       0  253.15    .035       0
Bank Sta=188.66,253.15
XS Rating Curve= 0 ,0
Exp/Cntr=0.3,0.1

Type RM Length L Ch R = 1 ,327.4682,124.13,327.54,124.31
XS GIS Cut Line= 3
    1079445.6949    1572613.6877    1079779.4184    1572790.7109
    1080103.7223    1572902.2829
#Sta/Elev= 18
       0   73.19   43.77    73.5  167.56    73.5   172.2      73  181.88      71
  187.32    70.5  190.49    70.5  198.68      71   208.4      72  218.86    73.5
  224.86      74  243.24      74  357.09    73.5     383    73.5  470.57   73.18
  549.23      73  668.55   73.04  720.73   73.49
#Mann= 3 , 0 , 0
       0    .035       0  167.56    .018       0  218.86    .035       0
Bank Sta=167.56,218.86
XS Rating Curve= 0 ,0
Exp/Cntr=0.3,0.1

River Reach=ARROYOELZORRO   ,ABAJOLAT1
Reach XY= 30
 1079528.51909681573013.86438046 1079327.72029681573037.67088046
 1078910.13529681572733.97148046 1078253.10579681572618.30508046
 1078094.25239681572733.38278046 1077901.52499681572656.19918046
 1077773.54629681572795.83678046 1077590.45549681572744.39078046
 1077195.64859681573072.34628046 1076992.29679681573064.68888046
 1076912.25779681573236.15908046 1076722.99529681573202.64758046
 1076612.41459681573358.39158046 1076411.53539681573301.74318046
 1076266.83699681573437.28828046 1076101.90009681573337.85438046
 1075934.87189681573443.29668046 1075776.39809681573325.96118046
 1075314.21129681573352.51228046 1075021.83569681573164.16158046
 1074762.10359681573307.02038046 1074809.06719681573474.36958046
 1074606.39599681573339.96098046 1074509.69059681573460.08208046
 1074467.14769681573329.44928046 1074343.85159681573398.90258046
 1074180.20649681573289.10028046 1074303.89949681573184.85428046
 1074009.94679681572948.05168046 1073636.69609681573264.44158046

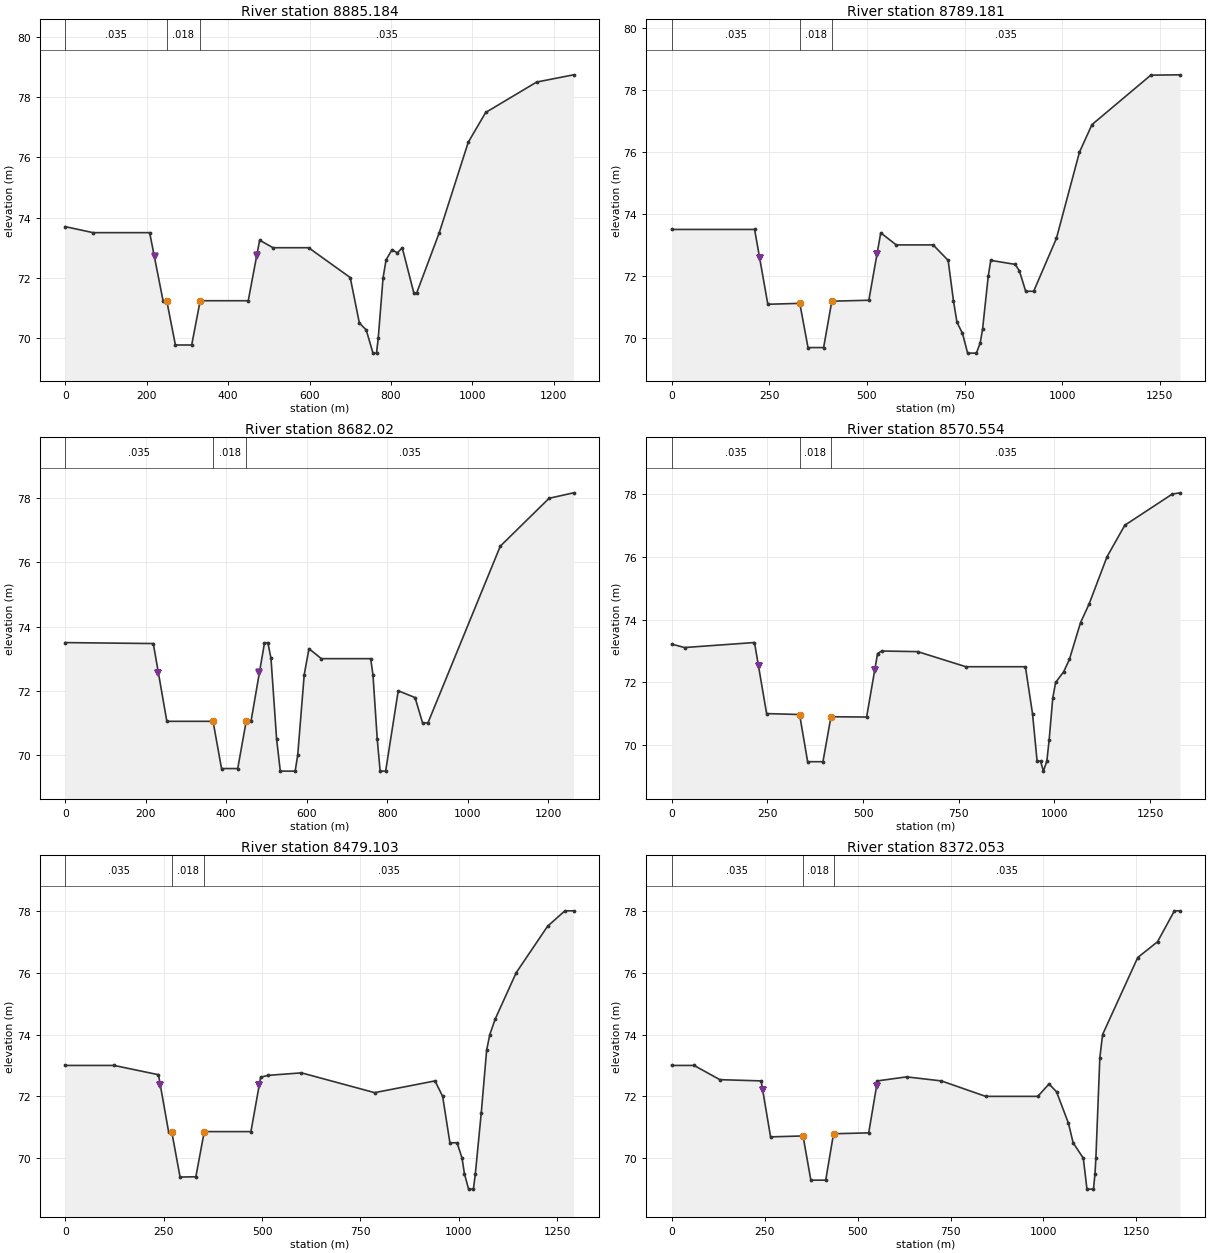
Type RM Length L Ch R = 1 ,8885.184,132.08,96,60.24
XS GIS Cut Line= 5
    1079689.4749    1572775.0158    1079573.3755    1572915.1394
    1079527.1627    1573013.1873     1079441.341    1573198.8588
    1079203.8048    1573913.9964
#Sta/Elev= 30
       0    73.7   68.38    73.5  207.42    73.5  240.31   71.24  249.34   71.24
  270.65   69.77  310.66   69.77  331.47   71.24  449.51   71.24  477.54   73.25
  510.44      73  597.78      73  699.99   72.01  722.46    70.5  739.33   70.27
  755.91    69.5  764.56    69.5  768.83      70  780.68      72  788.11    72.6
  802.42   72.93  815.94   72.83  827.78      73  856.22    71.5  863.31    71.5
  918.75    73.5  989.86    76.5 1032.67   77.49 1157.89    78.5 1248.47   78.74
#Mann= 3 , 0 , 0
       0    .035       0  249.34    .018       0  331.47    .035       0
Levee=-1,219.31,72.74111,-1,470.51,72.74126,	452,	451
Bank Sta=249.34,331.47
XS Rating Curve= 0 ,0
Exp/Cntr=0.3,0.1

Type RM Length L Ch R = 1 ,8789.181,71.26,107.16,143.04
XS GIS Cut Line= 5
    1079531.8761    1572688.6196    1079402.7592    1572950.0285
    1079453.2203    1573057.3448    1079460.9676    1573080.2037
    1079160.4004    1573894.0637
#Sta/Elev= 30
       0    73.5   212.4    73.5  246.26   71.08  328.15   71.11  349.15   69.68
  389.15   69.68  410.15   71.18  504.98   71.21  535.47   73.39  575.11      73
  669.62      73  708.06    72.5  721.73   71.19  730.62    70.5  744.79   70.14
  757.94    69.5  780.38    69.5  790.23   69.83  796.36   70.29  810.78   71.99
  817.23    72.5  879.82   72.37   890.5   72.16  906.69    71.5  927.07    71.5
  985.34   73.21 1044.39      76 1076.42   76.89 1227.07   78.49 1301.87    78.5
#Mann= 3 , 0 , 0
       0    .035       0  328.15    .018       0  410.15    .035       0
Levee=-1,225.26,72.58036,-1,526.05,72.71256,	452,	451
Bank Sta=328.15,410.15
XS Rating Curve= 0 ,0
Exp/Cntr=0.3,0.1

Type RM Length L Ch R = 1 ,8682.02 ,74.63,111.47,148.33
XS GIS Cut Line= 4
    1079486.3677    1572661.6321    1079419.3723    1572857.7406
    1079292.7963    1573129.7306    1079063.1393    1573850.2486
#Sta/Elev= 30
       0    73.5  218.95   73.47  252.64   71.05  367.49   71.05  388.54   69.58
  428.82   69.58  449.82   71.05  461.84   71.05  495.23   73.48  503.71    73.5
  511.46   73.01  525.43    70.5  534.64    69.5  571.54    69.5  577.94      70
  594.06    72.5   605.9   73.31  636.65      73  759.24      73  764.93    72.5
  775.55    70.5  782.78    69.5  796.46    69.5  827.74      72  869.52   71.79
  888.28      71  901.54      71 1081.42    76.5 1202.71   77.99 1263.47   78.16
#Mann= 3 , 0 , 0
       0    .035       0  367.49    .018       0  449.82    .035       0
Levee=-1,231.64,72.55075,-1,482.84,72.55075,	452,	451
Bank Sta=367.49,449.82
XS Rating Curve= 0 ,0
Exp/Cntr=0.3,0.1

Type RM Length L Ch R = 1 ,8570.554,128.33,91.45,54.52
XS GIS Cut Line= 6
    1079448.3734    1572649.6729    1079387.8709    1572843.0808
    1079344.2332    1572935.8468    1079236.2393    1572961.8225
     1079212.153    1572968.0202    1078982.7058    1573824.8486
#Sta/Elev= 30
       0   73.22   33.56   73.11  216.39   73.27  248.05   71.01  334.24   70.98
  355.24   69.48  395.24   69.48  416.24   70.91  509.33    70.9  537.96   72.92
  548.72      73  642.69   72.98  768.63    72.5  924.21    72.5  942.88      71
  954.78    69.5  963.72    69.5   971.2   69.18  980.22    69.5  986.24   70.17
  995.65    71.5 1003.15      72 1024.17   72.34 1039.11   72.73 1068.18    73.9
 1090.81    74.5 1137.54      76 1183.97      77 1307.88   77.99 1328.13   78.03
#Mann= 3 , 0 , 0
       0    .035       0  334.24    .018       0  416.24    .035       0
Levee=-1,227.05,72.51025,-1,530.65,72.40443,	452,	451
Bank Sta=334.24,416.24
XS Rating Curve= 0 ,0
Exp/Cntr=0.3,0.1

Type RM Length L Ch R = 1 ,8479.103,143.28,107.05,70.86
XS GIS Cut Line= 4
    1079359.4733    1572590.4061    1079272.7216    1572789.4938
    1079146.1456    1573061.4837    1078894.6523    1573793.5218
#Sta/Elev= 30
       0      73  124.03      73  236.91    72.7  262.57   70.86  270.55   70.86
  291.77   69.39  331.85    69.4  353.22   70.86  471.77   70.86  496.41   72.62
  515.77   72.68  600.11   72.76  786.04   72.12  939.38    72.5  958.72      72
  977.18    70.5  995.44    70.5 1008.04      70 1014.04    69.5  1024.6      69
 1036.88      69 1041.74   69.49 1056.77   71.46 1070.55    73.5 1078.59      74
 1092.19    74.5  1145.6      76 1225.17    77.5 1269.16      78  1291.2      78
#Mann= 3 , 0 , 0
       0    .035       0  270.55    .018       0  353.22    .035       0
Levee=-1,241.57,72.36261,-1,492.77,72.36261,	452,	451
Bank Sta=270.55,353.22
XS Rating Curve= 0 ,0
Exp/Cntr=0.3,0.1

Type RM Length L Ch R = 1 ,8372.053,72.42,108.66,144.91
XS GIS Cut Line= 6
    1079236.8122    1572529.6153    1079140.6199    1572728.0176
    1079096.0536    1572807.9575    1079149.5197     1572919.071
     1079160.612    1572940.2495    1078827.2364    1573784.8012
#Sta/Elev= 30
       0      73   60.21      73  129.66   72.54  240.63    72.5  266.01   70.69
  353.32   70.72  374.32   69.29  414.32   69.29  435.32   70.79  529.97   70.82
  553.46    72.5   631.7   72.63  725.27    72.5  844.52      72  984.74      72
 1014.89    72.4 1035.04   72.15 1067.22   71.13 1079.68    70.5 1107.13      70
 1116.99      69 1134.46      69  1138.6    69.5 1140.94      70  1151.6   73.25
 1159.01      74 1253.53   76.49 1306.77      77 1352.15      78  1367.2      78
#Mann= 3 , 0 , 0
       0    .035       0  353.32    .018       0  435.32    .035       0
Levee=-1,244.96,72.19109,-1,551.01,72.32472,	452,	451
Bank Sta=353.32,435.32
XS Rating Curve= 0 ,0
Exp/Cntr=0.3,0.1

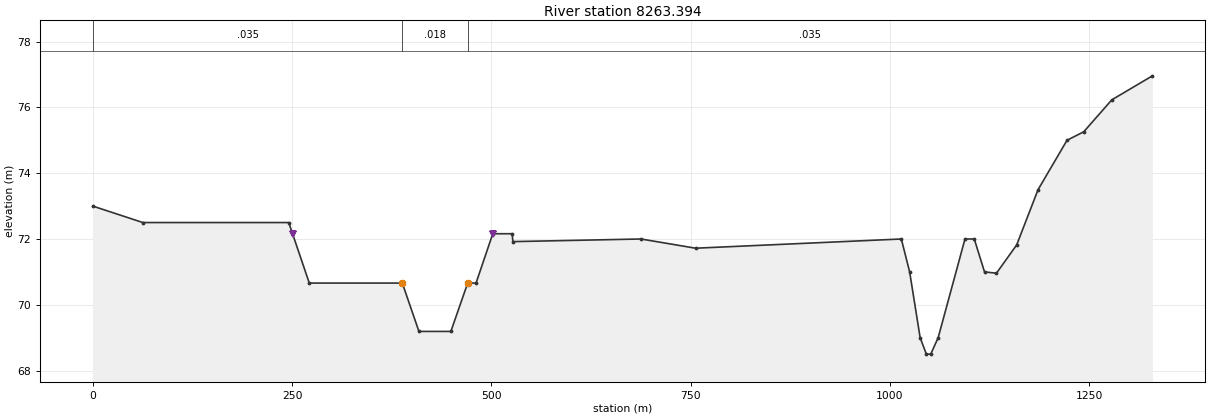
Type RM Length L Ch R = 1 ,8263.394,75.89,111.57,147.24
XS GIS Cut Line= 4
    1079207.1788    1572509.5069    1079114.7195    1572715.9643
    1078988.1435    1572987.9543    1078734.1028    1573749.8761
#Sta/Elev= 30
       0      73   62.84    72.5  245.85    72.5  271.62   70.66  388.31   70.66
  409.19   69.19  449.23   69.19  470.35   70.66  480.82   70.66  501.82   72.16
  526.22   72.16  526.96   71.92  687.74      72  756.24   71.72 1014.35      72
 1024.78      71 1037.96      69 1045.76    68.5 1051.26    68.5 1060.57      69
 1094.21      72 1105.86      72 1118.71      71  1133.7   70.96 1159.07   71.82
  1185.9    73.5  1222.2      75 1243.25   75.26  1278.4   76.23 1329.37   76.96
#Mann= 3 , 0 , 0
       0    .035       0  388.31    .018       0  470.35    .035       0
Levee=-1,250.61,72.15994,-1,501.81,72.15994,	452,	451
Bank Sta=388.31,470.35
XS Rating Curve= 0 ,0
Exp/Cntr=0.3,0.1