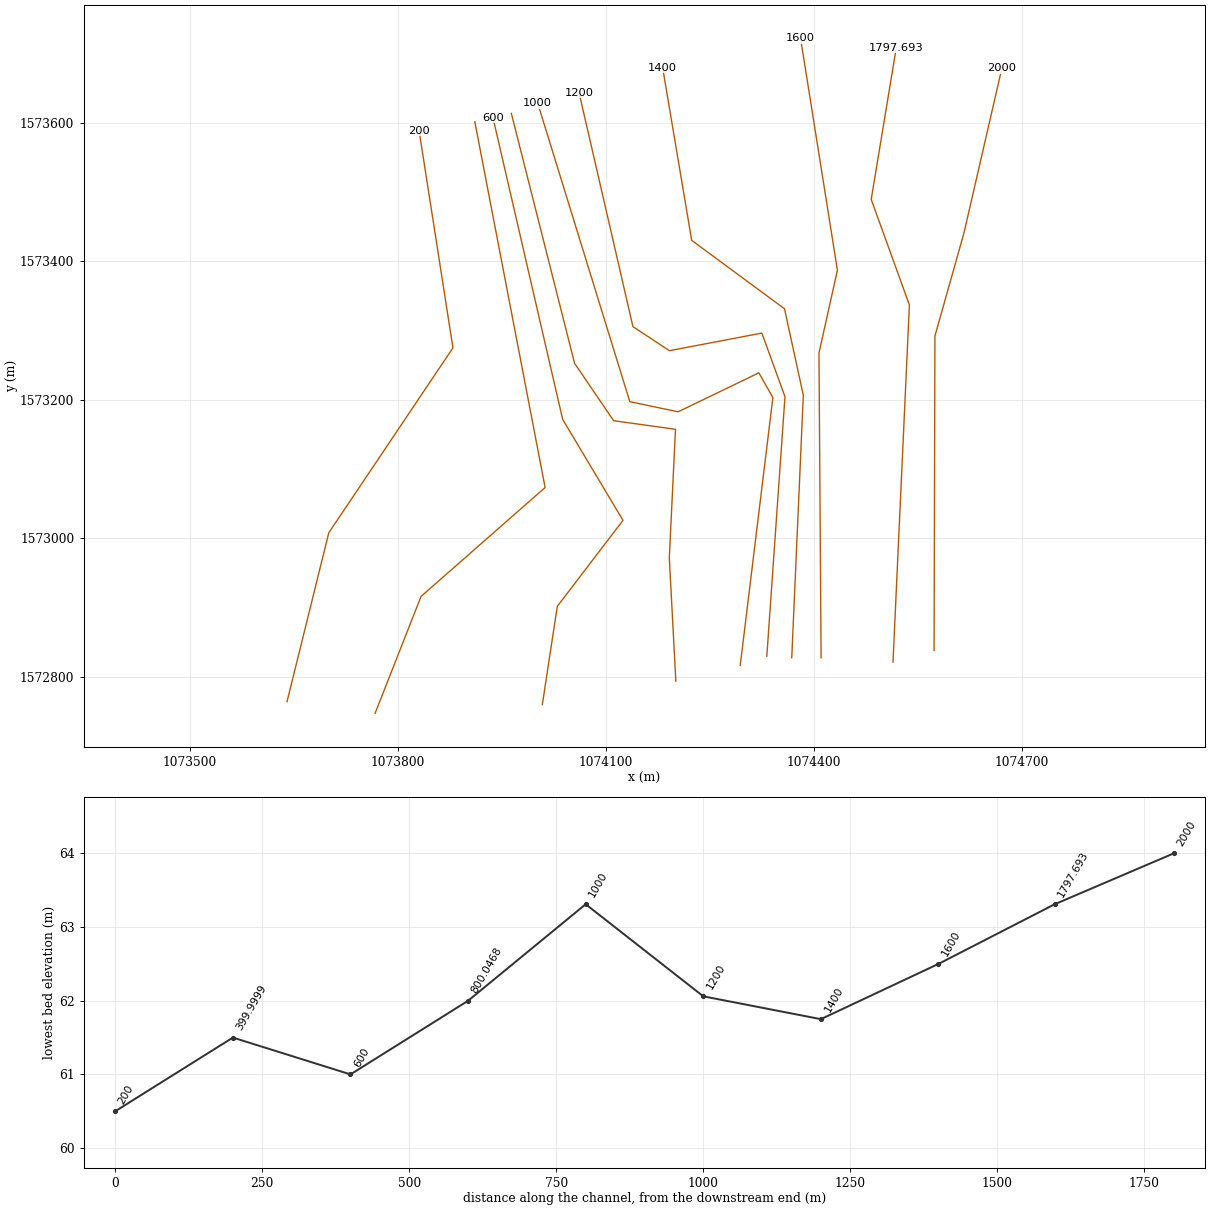
HEC-RAS study HECRAS_v2.prj: HECRAS_v2

--- HECRAS_v2.g01 (geometry) --- (continued)

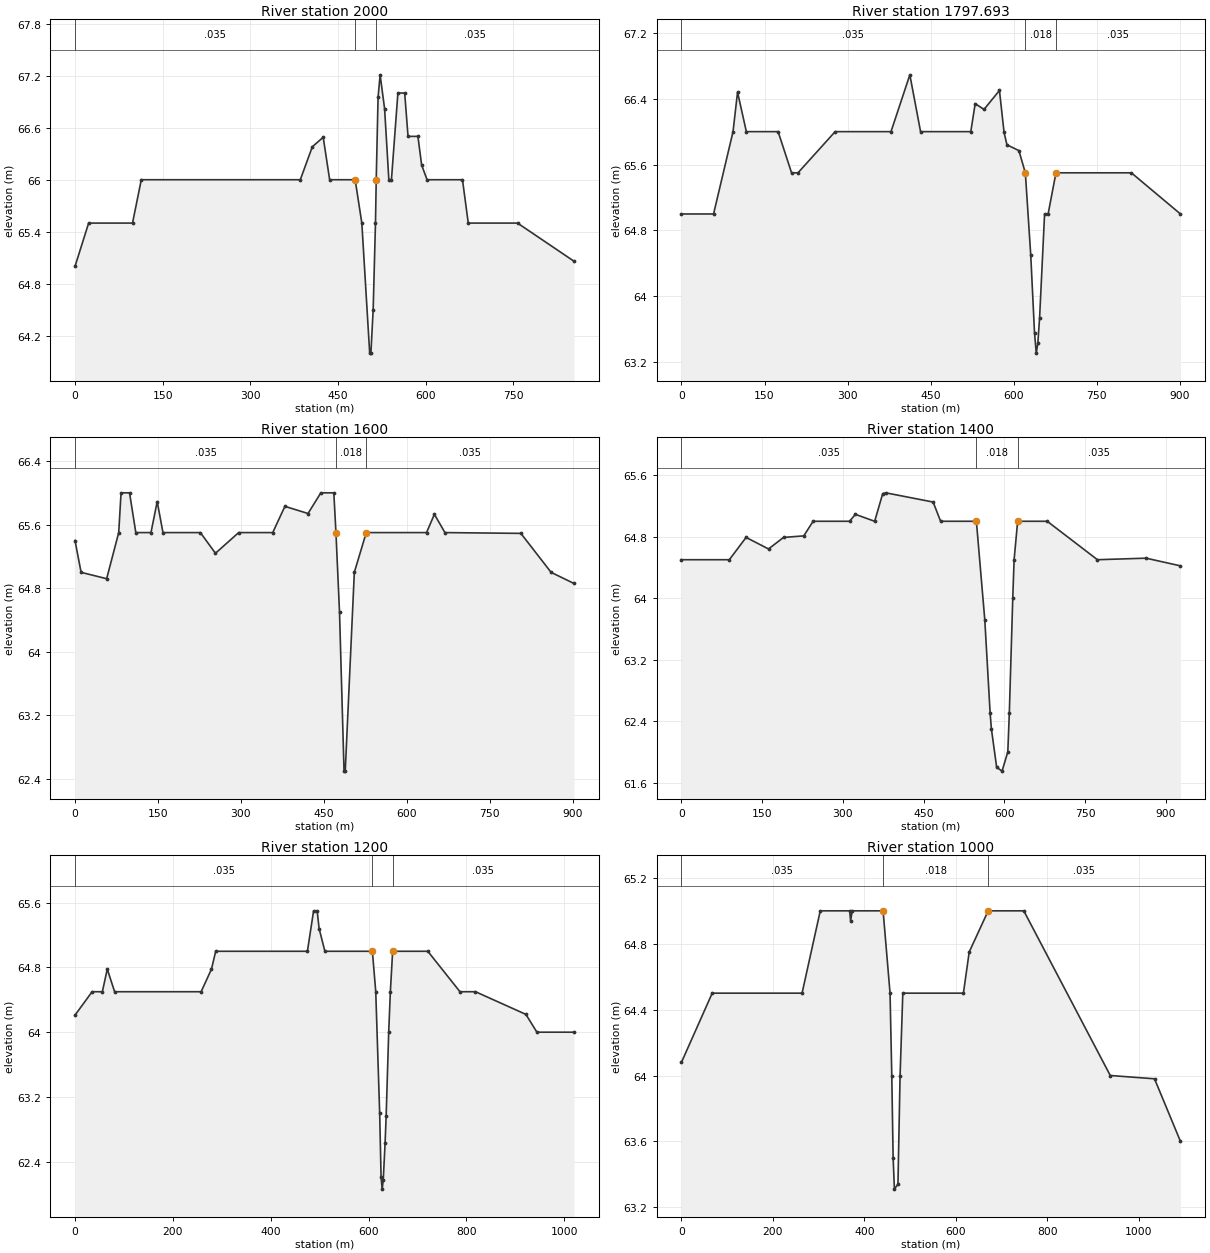
Type RM Length L Ch R = 1 ,2000    ,178.48,202.31,216.87
XS GIS Cut Line= 4
    1074573.7685    1572837.7829    1074574.9818    1573292.1952
    1074616.7788    1573440.8024    1074671.6646    1573679.6887
#Sta/Elev= 30
       0      65   23.35    65.5   98.44    65.5  113.46      66  385.56      66
  406.12   66.38  424.74   66.49  435.77      66   479.4      66  490.84    65.5
  504.29      64  506.36      64  510.23    64.5  514.19    65.5  515.48      66
  518.62   66.95  522.13   67.21  529.78   66.82  537.07      66  541.51      66
  552.55      67  564.19      67  569.89    66.5  586.83    66.5  593.16   66.17
  602.47      66  663.08      66  672.95    65.5  757.28    65.5   853.9   65.06
#Mann= 3 , 0 , 0
       0    .035       0   479.4    .018       0  515.48    .035       0
Bank Sta=479.4,515.48
XS Rating Curve= 0 ,0
Exp/Cntr=0.3,0.1

Type RM Length L Ch R = 1 ,1797.693,214.45,197.69,185.65
XS GIS Cut Line= 4
    1074514.5018    1572820.8495    1074538.1554    1573337.1533
    1074483.0853    1573489.6785    1074519.2643    1573709.0575
#Sta/Elev= 30
       0      65   57.98      65   93.17      66  101.31   66.48  117.22      66
   174.6      66  198.88    65.5   210.5    65.5  277.59      66  378.51      66
  412.53   66.69   431.9      66  522.64      66  530.54   66.34   546.5   66.27
  574.38    66.5  582.74   65.99  587.92   65.84  609.49   65.77  621.15    65.5
  630.92    64.5  637.71   63.56  640.84   63.31  643.73   63.43  646.92   63.74
  655.91      65  662.28      65  676.48    65.5  812.64    65.5  901.35      65
#Mann= 3 , 0 , 0
       0    .035       0  621.15    .018       0  676.48    .035       0
Bank Sta=621.15,676.48
XS Rating Curve= 0 ,0
Exp/Cntr=0.3,0.1

Type RM Length L Ch R = 1 ,1600    ,134.48,200,216.46
XS GIS Cut Line= 4
    1074410.7849    1572827.1995    1074407.7038    1573267.6814
     1074434.311    1573387.4131    1074381.1515    1573722.5513
#Sta/Elev= 30
       0    65.4   11.05      65   57.27   64.92   79.08    65.5   83.31      66
   98.66      66  109.99    65.5  137.43    65.5  148.67   65.89  159.11    65.5
  226.78    65.5  254.02   65.24  296.01    65.5  357.63    65.5  379.63   65.83
  421.45   65.74  444.65      66  468.11      66  471.94    65.5   478.4    64.5
  486.58    62.5  488.75    62.5   505.2      65  526.76    65.5  635.79    65.5
  649.99   65.73  669.06    65.5  806.39   65.49  861.06      65  902.47   64.86
#Mann= 3 , 0 , 0
       0    .035       0  471.94    .018       0  526.76    .035       0
Bank Sta=471.94,526.76
XS Rating Curve= 0 ,0
Exp/Cntr=0.3,0.1

Type RM Length L Ch R = 1 ,1400    ,66.77,200,200.75
XS GIS Cut Line= 5
    1074368.4515    1572827.1995    1074385.1202    1573206.6128
    1074357.9785    1573331.6301    1074224.0756    1573430.5995
    1074182.1844    1573680.2179
#Sta/Elev= 29
       0    64.5   88.97    64.5  120.09   64.79  161.81   64.64  189.73   64.79
   227.3   64.81  244.67      65  312.31      65  323.28   65.09  359.04      65
  374.04   65.36  379.78   65.37   467.7   65.25   481.6      65  548.07      65
  563.68   63.72  573.67    62.5  575.96    62.3  585.76    61.8  595.77   61.75
  606.47      62  609.26    62.5  615.68      64  618.19    64.5  624.74      65
  679.73      65  773.02    64.5  863.42   64.52  927.33   64.42
#Mann= 3 , 0 , 0
       0    .035       0  548.07    .018       0  624.74    .035       0
Bank Sta=548.07,624.74
XS Rating Curve= 0 ,0
Exp/Cntr=0.3,0.1

Type RM Length L Ch R = 1 ,1200    ,254.92,200,253.54
XS GIS Cut Line= 6
    1074332.4681    1572829.3162    1074358.6619    1573204.4961
    1074325.3532    1573296.4952    1074191.9693    1573271.0397
    1074139.3303     1573305.863    1074061.5342    1573644.2345
#Sta/Elev= 30
       0   64.21   34.97    64.5   55.95    64.5   65.98   64.78      81    64.5
  257.81    64.5  279.04   64.78  287.64      65  475.11      65  487.74    65.5
  494.99    65.5  499.05   65.28  510.83      65  607.92      65   614.8    64.5
  622.81      63  625.67   62.21  627.91   62.06  630.11   62.17  633.89   62.63
  636.05   62.96  641.27      64  644.66    64.5  649.32      65  721.23      65
  786.94    64.5  818.68    64.5  921.72   64.22  944.22      64 1020.04      64
#Mann= 3 , 0 , 0
       0    .035       0  607.92    .018       0  649.32    .035       0
Bank Sta=607.92,649.32
XS Rating Curve= 0 ,0
Exp/Cntr=0.3,0.1

Type RM Length L Ch R = 1 ,1000    ,294.09,199.95,86.36
XS GIS Cut Line= 6
    1074294.1034     1572816.087    1074341.2283    1573203.2294
    1074321.0168    1573239.0549    1074204.6368    1573182.7241
    1074134.8528    1573197.2763    1074002.0028     1573628.624
#Sta/Elev= 22
       0   64.08   67.22    64.5  263.62    64.5  303.38      65  367.67      65
  369.72   64.94  373.31      65  440.71      65  455.92    64.5   459.7      64
  462.65    63.5  465.46   63.31  473.18   63.34  477.84      64  483.82    64.5
  616.26    64.5  628.94   64.75   670.4      65  748.23      65  937.24      64
 1033.94   63.98 1090.67    63.6
#Mann= 3 , 0 , 0
       0    .035       0  440.71    .018       0   670.4    .035       0
Bank Sta=440.71,670.4
XS Rating Curve= 0 ,0
Exp/Cntr=0.3,0.1

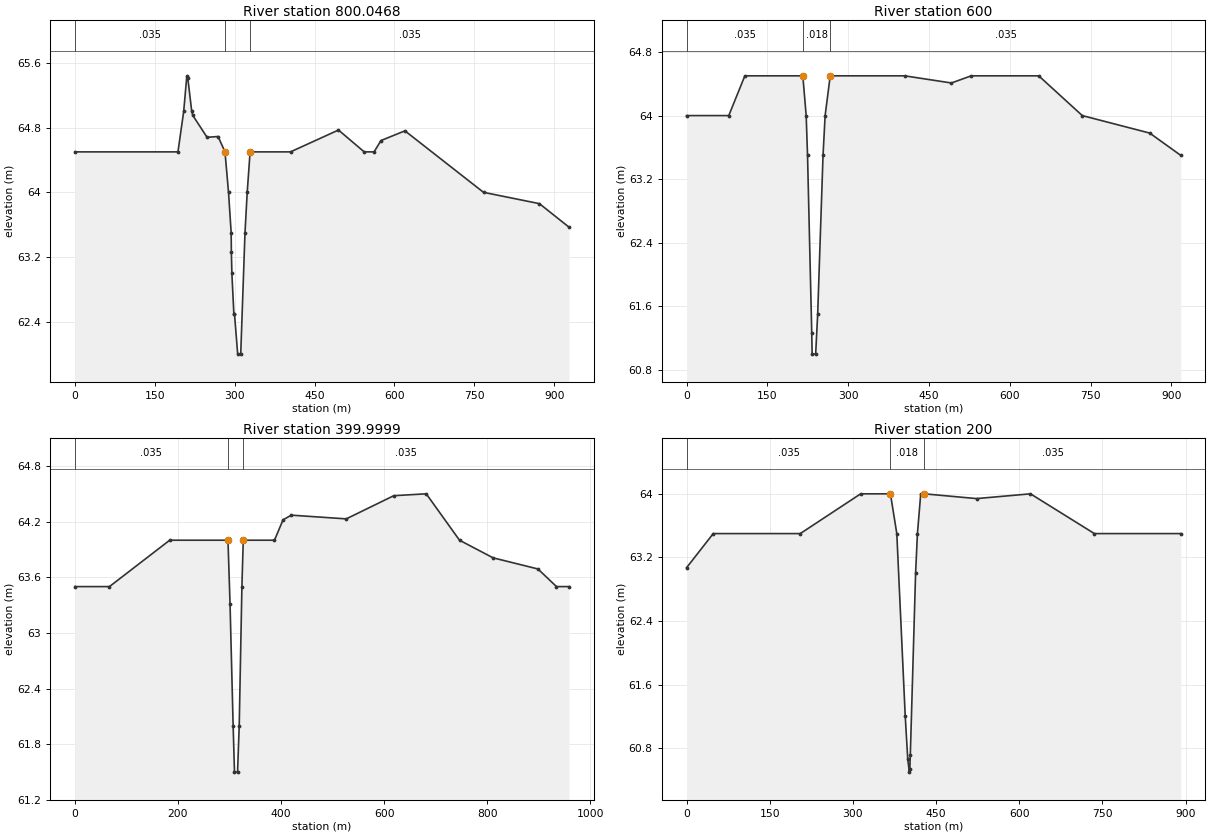
Type RM Length L Ch R = 1 ,800.0468,171.38,200.05,152.94
XS GIS Cut Line= 6
    1074201.2345    1572793.3328    1074191.8097    1572971.5487
    1074200.7204    1573157.4253    1074111.5405    1573169.8356
    1074055.1842    1573252.6504    1073963.9027    1573614.0719
#Sta/Elev= 30
       0    64.5  193.71    64.5  204.47      65  210.37   65.44  212.23   65.41
  219.55      65  221.63   64.95  248.33   64.68  268.99   64.69  281.96    64.5
   288.6      64  293.57    63.5  293.96   63.26  294.89      63  298.62    62.5
  299.76    62.5  305.81      62  311.51      62  319.51    63.5  323.67      64
  329.11    64.5  404.95    64.5  494.96   64.77  543.24    64.5  561.83    64.5
  574.71   64.64  619.69   64.76  767.17      64  872.09   63.86  927.54   63.57
#Mann= 3 , 0 , 0
       0    .035       0  281.96    .018       0  329.11    .035       0
Bank Sta=281.96,329.11
XS Rating Curve= 0 ,0
Exp/Cntr=0.3,0.1

Type RM Length L Ch R = 1 ,600     ,201.9,200,218.01
XS GIS Cut Line= 5
    1074008.6174     1572759.466    1074030.2323    1572901.4454
    1074124.9951    1573025.8185    1074037.9862    1573171.6877
    1073937.4443    1573607.7219
#Sta/Elev= 20
       0      64   78.46      64  108.31    64.5  215.89    64.5  222.13      64
  224.65    63.5  232.46   61.27  233.18      61  239.72      61  243.46    61.5
  253.42    63.5   257.3      64  266.76    64.5  404.91    64.5  491.72   64.41
  528.45    64.5  653.76    64.5  734.64      64  859.78   63.78   917.3    63.5
#Mann= 3 , 0 , 0
       0    .035       0  215.89    .018       0  266.76    .035       0
Bank Sta=215.89,266.76
XS Rating Curve= 0 ,0
Exp/Cntr=0.3,0.1

Type RM Length L Ch R = 1 ,399.9999,192.3,200,207.7
XS GIS Cut Line= 4
    1073767.3169     1572746.766    1073833.6822     1572915.828
    1074012.6483    1573073.2531    1073911.2505    1573601.9011
#Sta/Elev= 22
       0    63.5   67.28    63.5  184.11      64   297.1      64  301.12   63.31
  307.11      62  309.74    61.5  315.67    61.5  318.91      62  324.11    63.5
  326.74      64   387.3      64   403.9   64.22  419.97   64.27  526.46   64.23
  618.64   64.48  681.57    64.5  746.05      64  811.16   63.81   898.1   63.69
  934.08    63.5  958.26    63.5
#Mann= 3 , 0 , 0
       0    .035       0   297.1    .018       0  326.74    .035       0
Bank Sta=297.1,326.74
XS Rating Curve= 0 ,0
Exp/Cntr=0.3,0.1

Type RM Length L Ch R = 1 ,200     ,205.41,200,196.46
XS GIS Cut Line= 4
    1073640.3167    1572763.6994    1073700.5868    1573007.8409
    1073879.6812    1573275.1143    1073830.8171     1573589.201
#Sta/Elev= 19
       0   63.07   48.22    63.5  205.12    63.5     314      64  367.72      64
  379.18    63.5  394.34   61.21  398.95   60.66  401.86    60.5  402.68   60.54
  403.56   60.72  413.06      63  416.37    63.5  422.34      64  428.89      64
  523.01   63.94  620.22      64   735.4    63.5  891.07    63.5
#Mann= 3 , 0 , 0
       0    .035       0  367.72    .018       0  428.89    .035       0
Bank Sta=367.72,428.89
XS Rating Curve= 0 ,0
Exp/Cntr=0.3,0.1
LCMann Table=0

Chan Stop Cuts=-1
Use User Specified Reach Order=0
Composite Channel Slope=5

--- HECRAS_v2.g02 (geometry) ---

Geom Title=HECRAS_v2a
Program Version=5.03

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
River Reach=ARROYOELZORRO   ,ARRIBALAT1
Reach XY= 30
 1080707.43739681573339.58328046 1080237.79819681573498.13468046
 1079862.93129681573168.18948046 1079320.61779681573033.81938046
 1079221.68659681572869.42468046 1078253.10579681572618.30508046
 1078094.25239681572733.38278046 1077901.52499681572656.19918046
 1077773.54629681572795.83678046 1077590.45549681572744.39078046
 1077195.64859681573072.34628046 1076992.29679681573064.68888046
 1076912.25779681573236.15908046 1076722.99529681573202.64758046
 1076612.41459681573358.39158046 1076411.53539681573301.74318046
 1076266.83699681573437.28828046 1076101.90009681573337.85438046
 1075314.21129681573352.51228046 1075021.83569681573164.16158046
 1074762.10359681573307.02038046 1074809.06719681573474.36958046
 1074606.39599681573339.96098046 1074509.69059681573460.08208046
 1074467.14769681573329.44928046 1074343.85159681573398.90258046
 1074180.20649681573289.10028046 1074303.89949681573184.85428046
 1074009.94679681572948.05168046 1073636.69609681573264.44158046

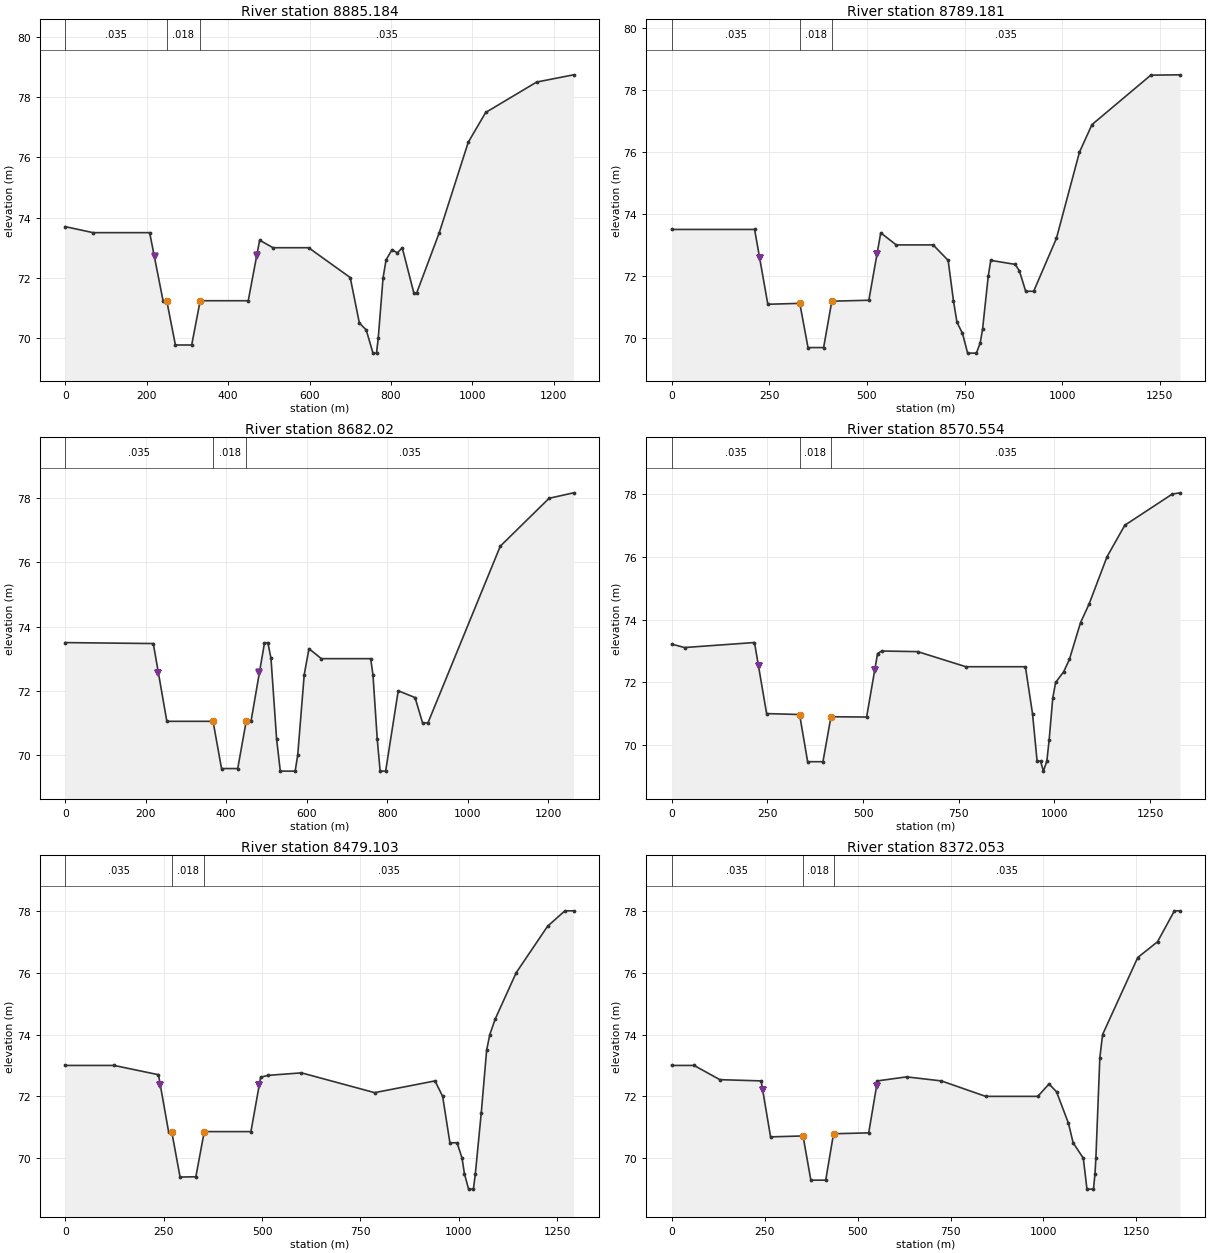
Type RM Length L Ch R = 1 ,8885.184,132.08,96,60.24
XS GIS Cut Line= 5
    1079689.4749    1572775.0158    1079573.3755    1572915.1394
    1079527.1627    1573013.1873     1079441.341    1573198.8588
    1079203.8048    1573913.9964
#Sta/Elev= 30
       0    73.7   68.38    73.5  207.42    73.5  240.31   71.24  249.34   71.24
  270.65   69.77  310.66   69.77  331.47   71.24  449.51   71.24  477.54   73.25
  510.44      73  597.78      73  699.99   72.01  722.46    70.5  739.33   70.27
  755.91    69.5  764.56    69.5  768.83      70  780.68      72  788.11    72.6
  802.42   72.93  815.94   72.83  827.78      73  856.22    71.5  863.31    71.5
  918.75    73.5  989.86    76.5 1032.67   77.49 1157.89    78.5 1248.47   78.74
#Mann= 3 , 0 , 0
       0    .035       0  249.34    .018       0  331.47    .035       0
Levee=-1,219.31,72.74111,-1,470.51,72.74126,	452,	451
Bank Sta=249.34,331.47
XS Rating Curve= 0 ,0
Exp/Cntr=0.3,0.1

Type RM Length L Ch R = 1 ,8789.181,71.26,107.16,143.04
XS GIS Cut Line= 5
    1079531.8761    1572688.6196    1079402.7592    1572950.0285
    1079453.2203    1573057.3448    1079460.9676    1573080.2037
    1079160.4004    1573894.0637
#Sta/Elev= 30
       0    73.5   212.4    73.5  246.26   71.08  328.15   71.11  349.15   69.68
  389.15   69.68  410.15   71.18  504.98   71.21  535.47   73.39  575.11      73
  669.62      73  708.06    72.5  721.73   71.19  730.62    70.5  744.79   70.14
  757.94    69.5  780.38    69.5  790.23   69.83  796.36   70.29  810.78   71.99
  817.23    72.5  879.82   72.37   890.5   72.16  906.69    71.5  927.07    71.5
  985.34   73.21 1044.39      76 1076.42   76.89 1227.07   78.49 1301.87    78.5
#Mann= 3 , 0 , 0
       0    .035       0  328.15    .018       0  410.15    .035       0
Levee=-1,225.26,72.58036,-1,526.05,72.71256,	452,	451
Bank Sta=328.15,410.15
XS Rating Curve= 0 ,0
Exp/Cntr=0.3,0.1

Type RM Length L Ch R = 1 ,8682.02 ,74.63,111.47,148.33
XS GIS Cut Line= 4
    1079486.3677    1572661.6321    1079419.3723    1572857.7406
    1079292.7963    1573129.7306    1079063.1393    1573850.2486
#Sta/Elev= 30
       0    73.5  218.95   73.47  252.64   71.05  367.49   71.05  388.54   69.58
  428.82   69.58  449.82   71.05  461.84   71.05  495.23   73.48  503.71    73.5
  511.46   73.01  525.43    70.5  534.64    69.5  571.54    69.5  577.94      70
  594.06    72.5   605.9   73.31  636.65      73  759.24      73  764.93    72.5
  775.55    70.5  782.78    69.5  796.46    69.5  827.74      72  869.52   71.79
  888.28      71  901.54      71 1081.42    76.5 1202.71   77.99 1263.47   78.16
#Mann= 3 , 0 , 0
       0    .035       0  367.49    .018       0  449.82    .035       0
Levee=-1,231.64,72.55075,-1,482.84,72.55075,	452,	451
Bank Sta=367.49,449.82
XS Rating Curve= 0 ,0
Exp/Cntr=0.3,0.1

Type RM Length L Ch R = 1 ,8570.554,128.33,91.45,54.52
XS GIS Cut Line= 6
    1079448.3734    1572649.6729    1079387.8709    1572843.0808
    1079344.2332    1572935.8468    1079236.2393    1572961.8225
     1079212.153    1572968.0202    1078982.7058    1573824.8486
#Sta/Elev= 30
       0   73.22   33.56   73.11  216.39   73.27  248.05   71.01  334.24   70.98
  355.24   69.48  395.24   69.48  416.24   70.91  509.33    70.9  537.96   72.92
  548.72      73  642.69   72.98  768.63    72.5  924.21    72.5  942.88      71
  954.78    69.5  963.72    69.5   971.2   69.18  980.22    69.5  986.24   70.17
  995.65    71.5 1003.15      72 1024.17   72.34 1039.11   72.73 1068.18    73.9
 1090.81    74.5 1137.54      76 1183.97      77 1307.88   77.99 1328.13   78.03
#Mann= 3 , 0 , 0
       0    .035       0  334.24    .018       0  416.24    .035       0
Levee=-1,227.05,72.51025,-1,530.65,72.40443,	452,	451
Bank Sta=334.24,416.24
XS Rating Curve= 0 ,0
Exp/Cntr=0.3,0.1

Type RM Length L Ch R = 1 ,8479.103,143.28,107.05,70.86
XS GIS Cut Line= 4
    1079359.4733    1572590.4061    1079272.7216    1572789.4938
    1079146.1456    1573061.4837    1078894.6523    1573793.5218
#Sta/Elev= 30
       0      73  124.03      73  236.91    72.7  262.57   70.86  270.55   70.86
  291.77   69.39  331.85    69.4  353.22   70.86  471.77   70.86  496.41   72.62
  515.77   72.68  600.11   72.76  786.04   72.12  939.38    72.5  958.72      72
  977.18    70.5  995.44    70.5 1008.04      70 1014.04    69.5  1024.6      69
 1036.88      69 1041.74   69.49 1056.77   71.46 1070.55    73.5 1078.59      74
 1092.19    74.5  1145.6      76 1225.17    77.5 1269.16      78  1291.2      78
#Mann= 3 , 0 , 0
       0    .035       0  270.55    .018       0  353.22    .035       0
Levee=-1,241.57,72.36261,-1,492.77,72.36261,	452,	451
Bank Sta=270.55,353.22
XS Rating Curve= 0 ,0
Exp/Cntr=0.3,0.1

Type RM Length L Ch R = 1 ,8372.053,72.42,108.66,144.91
XS GIS Cut Line= 6
    1079236.8122    1572529.6153    1079140.6199    1572728.0176
    1079096.0536    1572807.9575    1079149.5197     1572919.071
     1079160.612    1572940.2495    1078827.2364    1573784.8012
#Sta/Elev= 30
       0      73   60.21      73  129.66   72.54  240.63    72.5  266.01   70.69
  353.32   70.72  374.32   69.29  414.32   69.29  435.32   70.79  529.97   70.82
  553.46    72.5   631.7   72.63  725.27    72.5  844.52      72  984.74      72
 1014.89    72.4 1035.04   72.15 1067.22   71.13 1079.68    70.5 1107.13      70
 1116.99      69 1134.46      69  1138.6    69.5 1140.94      70  1151.6   73.25
 1159.01      74 1253.53   76.49 1306.77      77 1352.15      78  1367.2      78
#Mann= 3 , 0 , 0
       0    .035       0  353.32    .018       0  435.32    .035       0
Levee=-1,244.96,72.19109,-1,551.01,72.32472,	452,	451
Bank Sta=353.32,435.32
XS Rating Curve= 0 ,0
Exp/Cntr=0.3,0.1

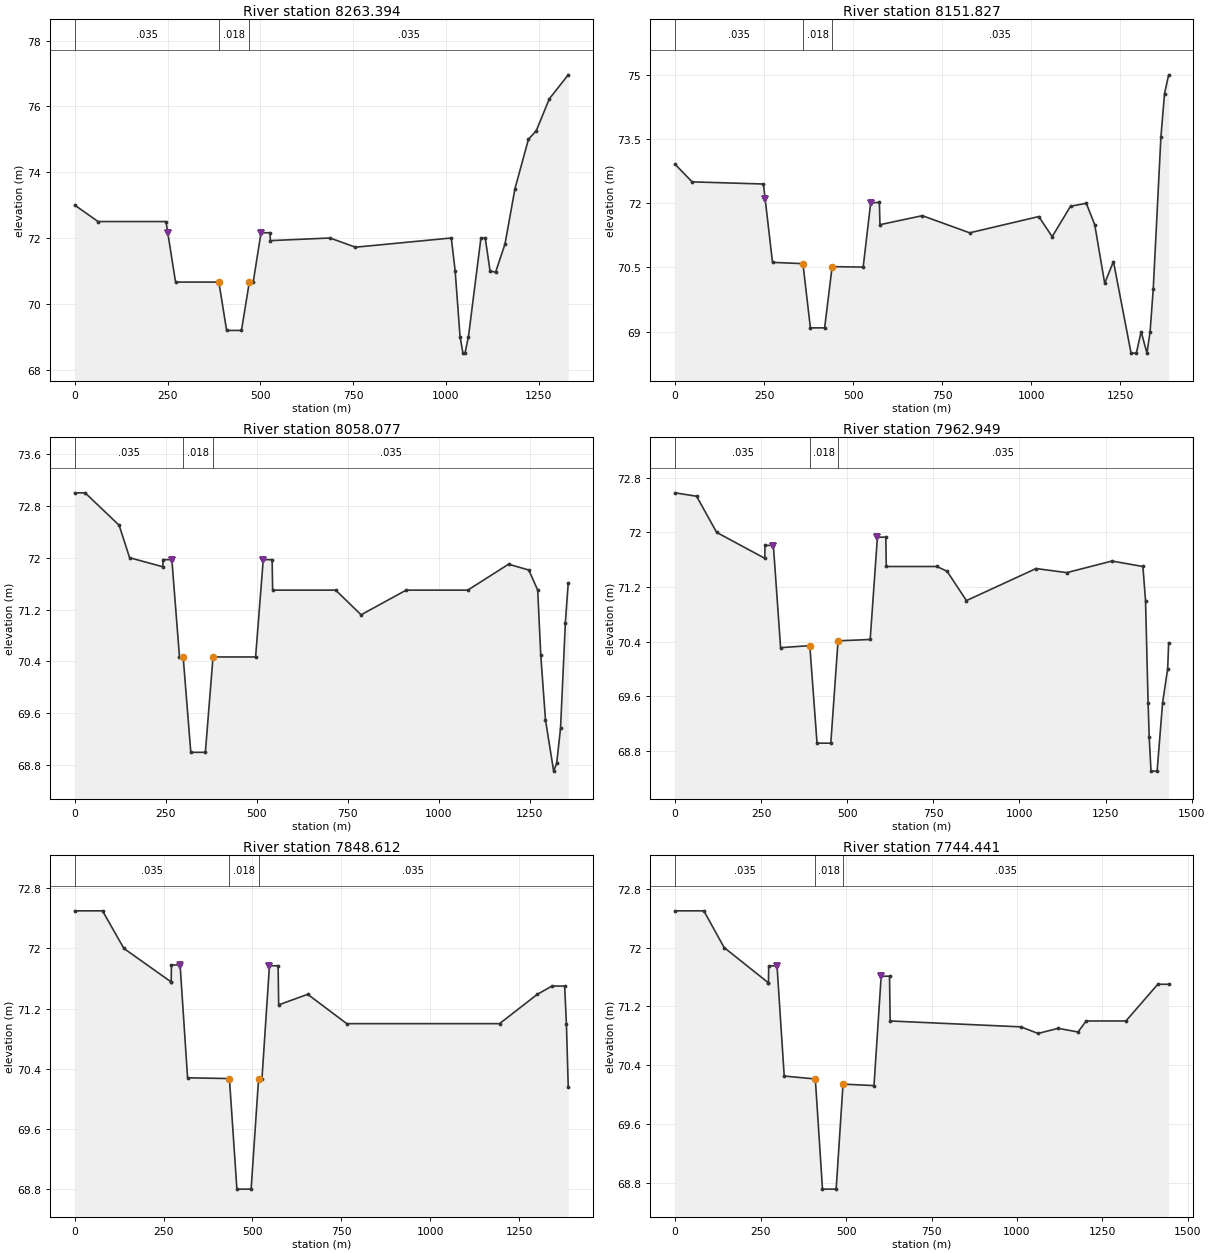
Type RM Length L Ch R = 1 ,8263.394,75.89,111.57,147.24
XS GIS Cut Line= 4
    1079207.1788    1572509.5069    1079114.7195    1572715.9643
    1078988.1435    1572987.9543    1078734.1028    1573749.8761
#Sta/Elev= 30
       0      73   62.84    72.5  245.85    72.5  271.62   70.66  388.31   70.66
  409.19   69.19  449.23   69.19  470.35   70.66  480.82   70.66  501.82   72.16
  526.22   72.16  526.96   71.92  687.74      72  756.24   71.72 1014.35      72
 1024.78      71 1037.96      69 1045.76    68.5 1051.26    68.5 1060.57      69
 1094.21      72 1105.86      72 1118.71      71  1133.7   70.96 1159.07   71.82
  1185.9    73.5  1222.2      75 1243.25   75.26  1278.4   76.23 1329.37   76.96
#Mann= 3 , 0 , 0
       0    .035       0  388.31    .018       0  470.35    .035       0
Levee=-1,250.61,72.15994,-1,501.81,72.15994,	452,	451
Bank Sta=388.31,470.35
XS Rating Curve= 0 ,0
Exp/Cntr=0.3,0.1

Type RM Length L Ch R = 1 ,8151.827,132.49,93.75,55.01
XS GIS Cut Line= 6
    1079179.6621    1572494.6902    1079087.3428     1572703.224
    1079045.2535    1572789.9658    1078932.8887    1572820.4592
    1078914.0199    1572841.8243    1078634.6193     1573714.951
#Sta/Elev= 30
       0   72.91   47.57    72.5  247.93   72.45  273.46   70.62   358.9   70.59
   379.9   69.09   419.9   69.09   440.9   70.52  528.14   70.51   549.2   72.01
  573.68   72.02  575.23    71.5  694.23   71.71  827.29   71.31  1021.3   71.69
 1058.96   71.22 1110.43   71.93 1154.79      72 1178.52    71.5 1206.48   70.13
 1231.08   70.64 1280.53    68.5 1295.36    68.5 1308.85      69 1325.22    68.5
 1333.96      69 1342.84      70 1364.31   73.54 1374.45   74.56 1386.14      75
#Mann= 3 , 0 , 0
       0    .035       0   358.9    .018       0   440.9    .035       0
Levee=-1,252.93,72.09,-1,549.29,72.01389,	452,	451
Bank Sta=358.9,440.9
XS Rating Curve= 0 ,0
Exp/Cntr=0.3,0.1

Type RM Length L Ch R = 1 ,8058.077,133.73,95.13,56.53
XS GIS Cut Line= 4
    1079064.8327    1572431.4018    1078954.4105    1572645.2909
    1078864.4802    1572883.4531     1078573.765     1573693.996
#Sta/Elev= 30
       0      73   28.62      73  122.09    72.5  150.84      72  242.23   71.86
  242.56   71.97  266.96   71.97  287.96   70.47  298.06   70.47  319.05      69
  359.06      69  380.13   70.47  497.16   70.47  518.16   71.97  542.56   71.97
  543.98    71.5  717.22    71.5  787.06   71.12  910.99    71.5 1080.33    71.5
 1192.41    71.9 1247.99   71.81 1272.48    71.5 1280.85    70.5 1293.84    69.5
 1316.32   68.71 1324.62   68.83 1335.22   69.37  1348.5      71 1356.39   71.61
#Mann= 3 , 0 , 0
       0    .035       0  298.06    .018       0  380.13    .035       0
Levee=-1,267.02,71.96507,-1,518.24,71.9697,	452,	451
Bank Sta=298.06,380.13
XS Rating Curve= 0 ,0
Exp/Cntr=0.3,0.1

Type RM Length L Ch R = 1 ,7962.949,78.48,114.34,150.19
XS GIS Cut Line= 6
    1078881.4231    1572348.1108    1078808.8085    1572598.7291
    1078784.9029    1572683.3915    1078852.9902    1572787.2213
    1078860.2564    1572814.6251    1078534.2891    1573687.5401
#Sta/Elev= 30
       0   72.58   62.27   72.53  120.53      72   260.3   71.62  260.85   71.81
  285.25   71.81  306.25   70.31  391.06   70.34  412.06   68.91  452.06   68.91
  473.06   70.41  566.41   70.43  587.41   71.93  611.82   71.93  613.12    71.5
  760.06    71.5  789.68   71.43  846.01      71 1048.08   71.47 1137.27   71.41
  1268.4   71.58 1358.38    71.5 1366.04      71 1373.51    69.5 1376.66      69
 1381.93    68.5 1399.68    68.5 1415.51    69.5 1430.31      70  1433.2   70.38
#Mann= 3 , 0 , 0
       0    .035       0  391.06    .018       0  473.06    .035       0
Levee=-1,285.33,71.8001,-1,587.45,71.93429,	452,	451
Bank Sta=391.06,473.06
XS Rating Curve= 0 ,0
Exp/Cntr=0.3,0.1

Type RM Length L Ch R = 1 ,7848.612,69.71,104.17,138.64
XS GIS Cut Line= 4
    1078856.8697    1572329.4841    1078785.7915    1572590.9508
    1078698.8347    1572878.1138    1078462.3223    1573660.4468
#Sta/Elev= 24
       0    72.5   78.19    72.5  138.34      72   269.6   71.56  271.41   71.56
  272.06   71.78  296.47   71.78  317.48   70.28  435.19   70.27  456.24    68.8
  496.27    68.8  517.26   70.27  526.77   70.27  547.78   71.77  572.19   71.77
  573.73   71.25  655.46   71.39   765.3      71 1195.07      71 1301.31   71.39
 1342.69    71.5  1378.2    71.5 1383.16      71  1388.3   70.16
#Mann= 3 , 0 , 0
       0    .035       0  435.19    .018       0  517.26    .035       0
Levee=-1,296.55,71.77283,-1,547.83,71.7709,	452,	451
Bank Sta=435.19,517.26
XS Rating Curve= 0 ,0
Exp/Cntr=0.3,0.1

Type RM Length L Ch R = 1 ,7744.441,136.14,96.57,56.98
XS GIS Cut Line= 6
     1078809.668    1572315.7257    1078755.1603    1572583.9023
    1078732.1978    1572678.9464    1078622.8718     1572729.903
    1078603.9276    1572741.1766    1078396.2822    1573647.3234
#Sta/Elev= 25
       0    72.5   83.96    72.5  143.29      72  272.73   71.52  273.01   71.52
  273.66   71.75  298.06   71.75  319.07   70.25  410.06   70.21  431.06   68.71
  471.06   68.71  491.13   70.14  492.06   70.14  581.73   70.12   602.7   71.61
  627.12   71.61  628.96      71 1011.28   70.92 1061.62   70.83 1120.55    70.9
 1178.57   70.85 1202.39      71  1318.7      71 1411.92    71.5 1443.73    71.5
#Mann= 3 , 0 , 0
       0    .035       0  410.06    .018       0  492.06    .035       0
Levee=-1,298.06,71.74581,-1,602.75,71.61491,	452,	451
Bank Sta=410.06,492.06
XS Rating Curve= 0 ,0
Exp/Cntr=0.3,0.1

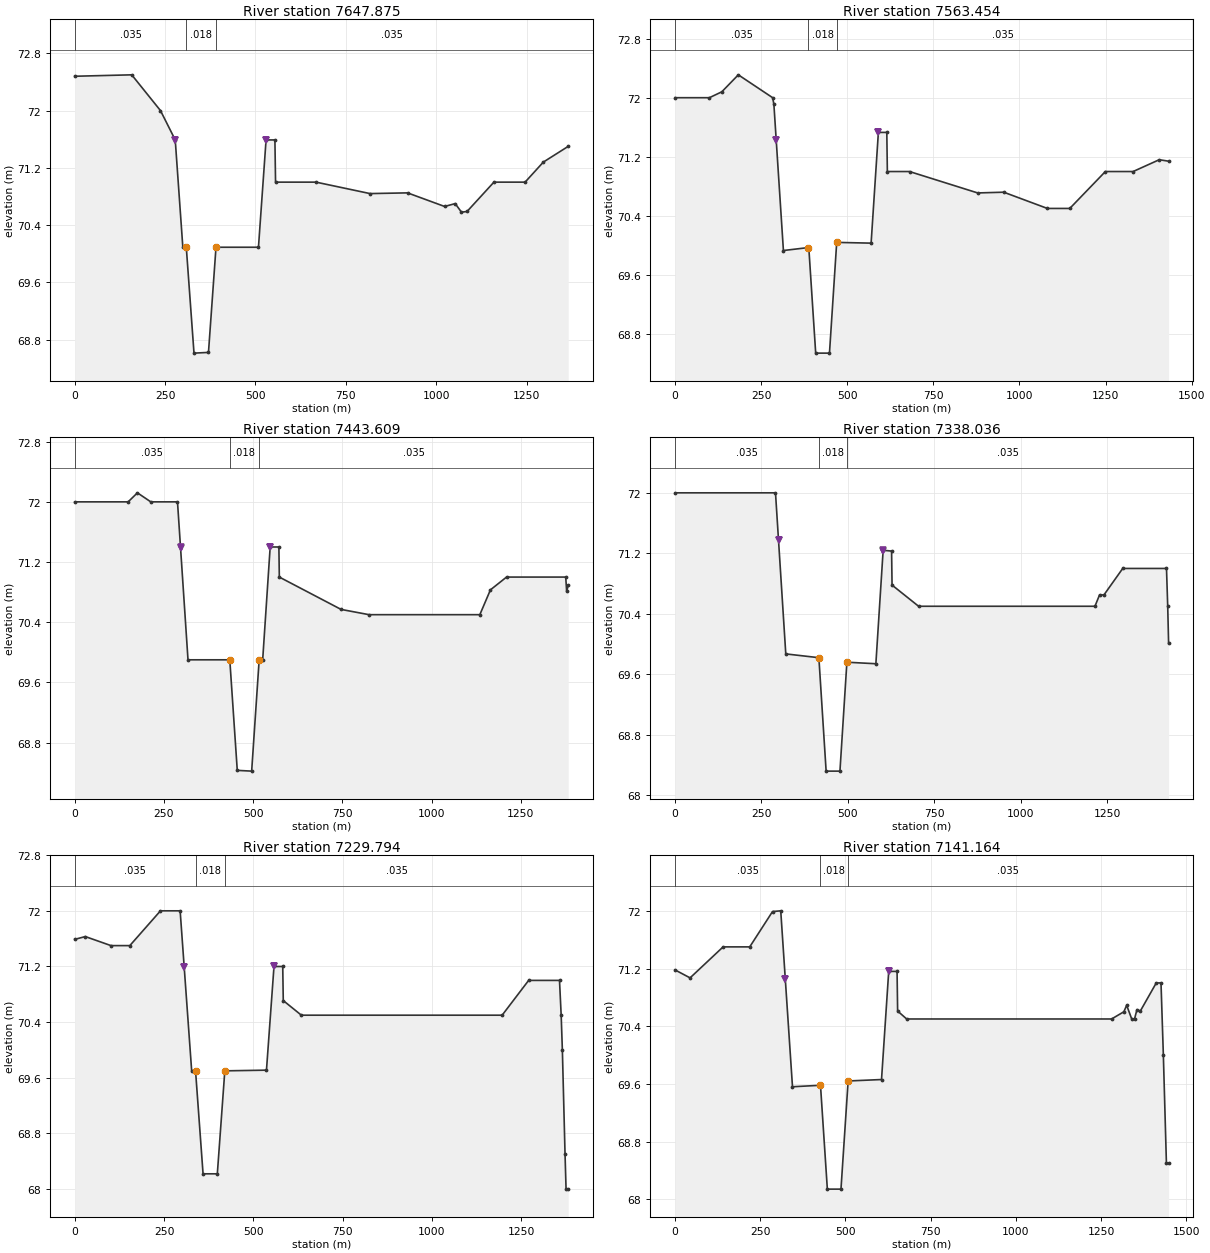
Type RM Length L Ch R = 1 ,7647.875,123.11,84.42,45.74
XS GIS Cut Line= 4
     1078660.612     1572303.449    1078611.3139    1572552.2751
    1078568.3847    1572803.1983    1078364.2781    1573635.2584
#Sta/Elev= 24
       0   72.48  157.71    72.5  237.24      72  278.04   71.59  299.04   70.09
  308.61   70.09  329.93   68.61  369.98   68.62  390.79   70.09  508.24   70.09
  529.28   71.59  553.73   71.59   555.5      71  667.43      71  816.89   70.84
  920.58   70.85 1023.06   70.66 1052.44    70.7 1069.75   70.58  1085.2   70.59
  1159.5      71 1245.72      71 1296.12   71.28 1364.96    71.5
#Mann= 3 , 0 , 0
       0    .035       0  308.61    .018       0  390.79    .035       0
Levee=-1,278.06,71.58556,-1,529.34,71.58855,	452,	451
Bank Sta=308.61,390.79
XS Rating Curve= 0 ,0
Exp/Cntr=0.3,0.1

Type RM Length L Ch R = 1 ,7563.454,84.95,119.85,154.72
XS GIS Cut Line= 5
     1078506.095     1572265.349    1078465.0065    1572577.1945
     1078464.185    1572614.5997    1078546.1793     1572698.458
    1078316.2297    1573634.4117
#Sta/Elev= 25
       0      72   99.46      72  135.64   72.08  183.54   72.31  283.25      72
  286.83   71.91  314.49   69.93  387.24   69.97  388.18   69.97  408.24   68.54
  448.24   68.54  469.24   70.04  569.16   70.03  590.24   71.53  614.73   71.53
  616.32      71  680.66      71  878.59   70.71  954.32   70.72 1081.03    70.5
 1146.05    70.5 1249.41      71 1329.96      71 1405.85   71.16 1433.03   71.14
#Mann= 3 , 0 , 0
       0    .035       0  387.24    .018       0  469.24    .035       0
Levee=-1,293.57,71.42873,-1,590.23,71.52978,	452,	451
Bank Sta=387.24,469.24
XS Rating Curve= 0 ,0
Exp/Cntr=0.3,0.1

Type RM Length L Ch R = 1 ,7443.609,70.34,105.57,140.83
XS GIS Cut Line= 4
     1078465.455    1572258.3639    1078431.9017    1572573.9409
    1078412.4907    1572827.8406    1078269.2396    1573625.5217
#Sta/Elev= 22
       0      72  149.71      72  175.66   72.12   213.1      72  287.93      72
  317.36    69.9  434.41    69.9  455.37   68.43   495.7   68.42  516.72    69.9
  526.57    69.9  547.57    71.4  571.97    71.4  573.18      71  746.15   70.57
  824.51    70.5  1134.9    70.5 1164.56   70.83  1209.7      71 1375.52      71
 1378.08   70.81 1382.44   70.89
#Mann= 3 , 0 , 0
       0    .035       0  434.41    .018       0  516.72    .035       0
Levee=-1,296.43,71.39285,-1,547.59,71.40041,	452,	451
Bank Sta=434.41,516.72
XS Rating Curve= 0 ,0
Exp/Cntr=0.3,0.1

Type RM Length L Ch R = 1 ,7338.036,148.73,108.24,67.75
XS GIS Cut Line= 6
    1078440.6899    1572253.2839    1078410.0467     1572572.214
    1078402.5898    1572626.6647     1078303.739    1572699.4352
    1078288.2896    1572714.9299    1078224.1545    1573621.0767
#Sta/Elev= 20
       0      72  290.56      72  320.33   69.87  416.11   69.82  437.11   68.32
  477.11   68.32   497.2   69.76  498.11   69.76   581.1   69.74  602.14   71.24
  626.59   71.23  627.94   70.78  704.78    70.5 1215.23    70.5  1228.5   70.65
 1241.25   70.65 1295.63      71 1422.31      71 1425.83    70.5  1428.4   70.01
#Mann= 3 , 0 , 0
       0    .035       0  416.11    .018       0  498.11    .035       0
Levee=-1,299.31,71.37502,-1,602.22,71.23528,	452,	451
Bank Sta=416.11,498.11
XS Rating Curve= 0 ,0
Exp/Cntr=0.3,0.1

Type RM Length L Ch R = 1 ,7229.794,125.27,88.63,51.99
XS GIS Cut Line= 4
    1078259.0796    1572239.3139    1078248.9277    1572576.7524
    1078259.1448    1572775.2182    1078191.1344    1573617.9017
#Sta/Elev= 24
       0   71.59   29.72   71.63   101.6    71.5   154.3    71.5  240.12      72
   295.2      72  327.46    69.7  338.32    69.7  359.36   68.22   399.3   68.22
  420.26    69.7   536.9   69.71  557.97    71.2  582.45    71.2  583.94   70.71
   634.6    70.5 1196.78    70.5 1270.95      71 1357.37      71 1362.04    70.5
 1365.39      70 1372.89    68.5 1375.74      68 1381.74      68
#Mann= 3 , 0 , 0
       0    .035       0  338.32    .018       0  420.26    .035       0
Levee=-1,306.5,71.19247,-1,558.01,71.2039,	452,	451
Bank Sta=338.32,420.26
XS Rating Curve= 0 ,0
Exp/Cntr=0.3,0.1

Type RM Length L Ch R = 1 ,7141.164,78.58,113.31,148.04
XS GIS Cut Line= 6
    1078140.9693    1572227.8839    1078125.4875    1572526.2204
    1078118.7443    1572619.6797    1078212.2914    1572687.2832
    1078230.5045    1572701.5948    1078163.1944    1573616.6317
#Sta/Elev= 29
       0   71.18   43.91   71.07  140.93    71.5  219.06    71.5  285.94   71.99
  310.04      72  344.53   69.56  425.86   69.58  426.73   69.58  446.86   68.14
  486.86   68.14  507.86   69.64  605.87   69.66  626.97   71.16  651.49   71.16
  653.15   70.61  679.69    70.5 1281.23    70.5  1317.2    70.6 1325.42   70.69
 1340.26    70.5 1348.49    70.5 1355.67   70.63 1365.51   70.61 1412.31      71
 1426.23      71 1433.13      70 1442.11    68.5 1448.53    68.5
#Mann= 3 , 0 , 0
       0    .035       0  425.86    .018       0  507.86    .035       0
Levee=-1,323.4,71.05342,-1,626.99,71.16149,	452,	451
Bank Sta=425.86,507.86
XS Rating Curve= 0 ,0
Exp/Cntr=0.3,0.1

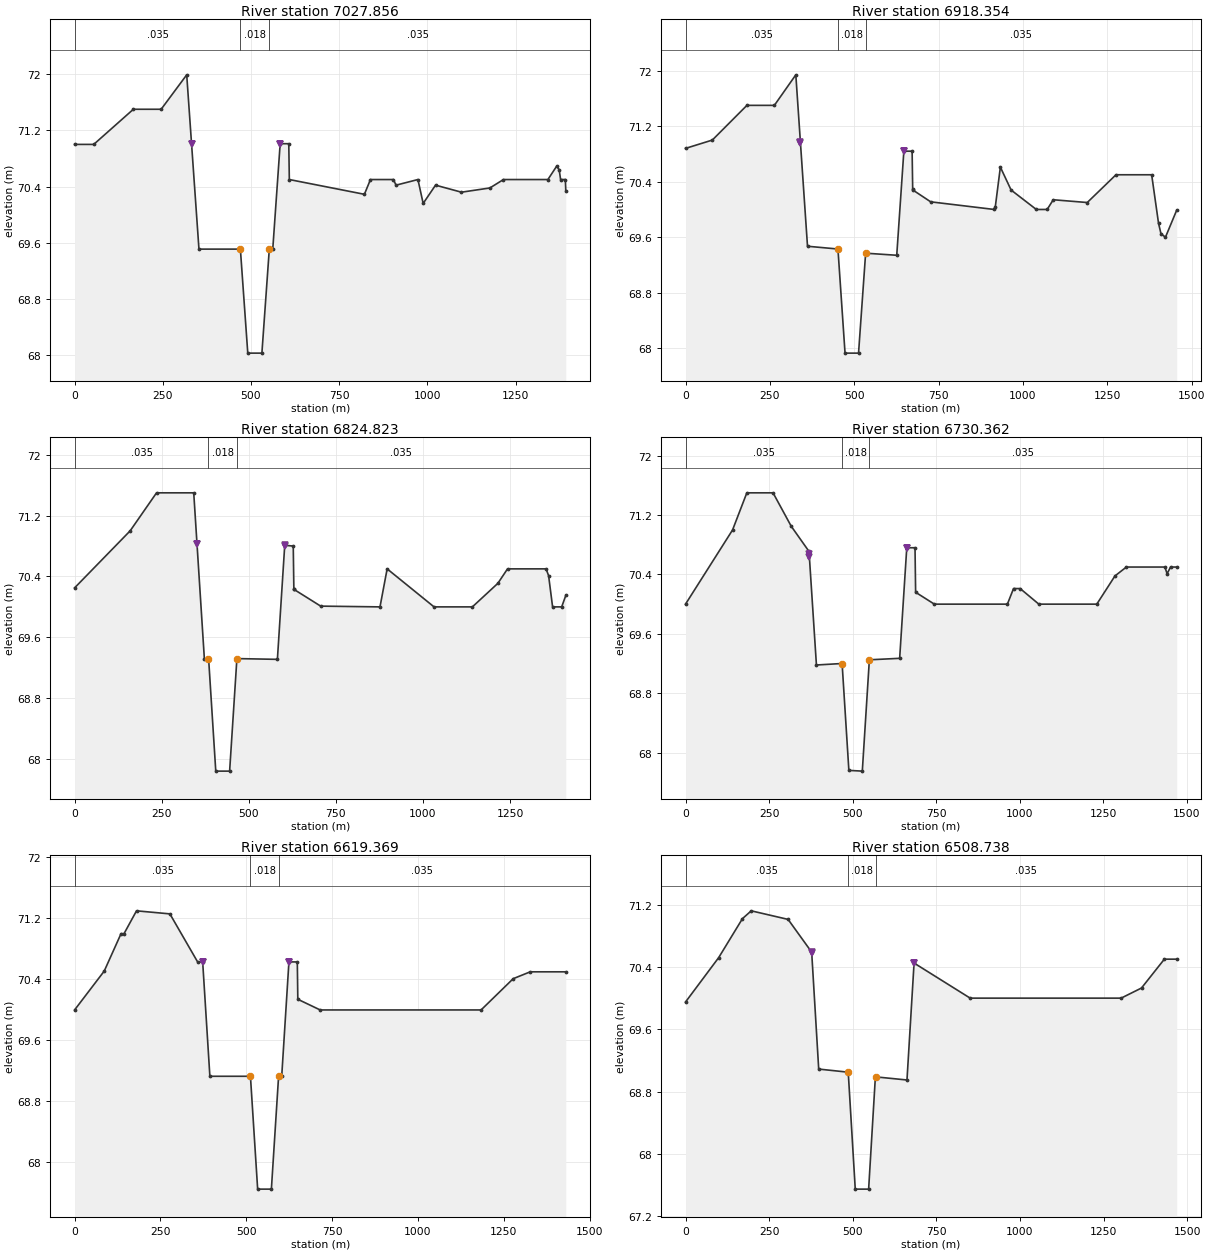
Type RM Length L Ch R = 1 ,7027.856,73.22,109.5,145.78
XS GIS Cut Line= 5
    1078089.5342    1572224.0739    1078072.2662    1572530.7353
    1078091.3989    1572692.3778    1078104.8158    1572829.0109
    1078096.5192    1573614.0916
#Sta/Elev= 30
       0      71   54.24      71  166.58    71.5  245.34    71.5  317.79   71.99
   352.5   69.51  469.92   69.51  490.89   68.03   530.9   68.03  551.91   69.51
  561.72   69.51  582.72   71.01  607.12   71.01  608.66    70.5  821.48   70.29
  838.62    70.5  903.76    70.5  911.13   70.42   973.2    70.5  988.04   70.16
 1023.09   70.42 1096.64   70.32 1177.09   70.38 1215.63    70.5 1341.61    70.5
 1366.45   70.69 1373.55   70.64 1377.63    70.5 1391.08    70.5 1392.33   70.34
#Mann= 3 , 0 , 0
       0    .035       0  469.92    .018       0  551.91    .035       0
Levee=-1,331.55,71.00288,-1,582.81,71.00985,	452,	451
Bank Sta=469.92,551.91
XS Rating Curve= 0 ,0
Exp/Cntr=0.3,0.1

Type RM Length L Ch R = 1 ,6918.354,130.83,93.53,56.23
XS GIS Cut Line= 6
    1078023.5364    1572218.3589    1078045.1515    1572579.2561
    1078058.2498    1572629.2047    1077972.8051    1572714.3585
    1077960.4596    1572730.8049    1078039.1998    1573628.6967
#Sta/Elev= 30
       0   70.88   79.45      71  181.95    71.5   263.3    71.5   326.9   71.94
  361.54   69.47  451.75   69.43  472.77   67.93   512.8   67.93  533.81   69.37
     626   69.34  647.09   70.84  671.59   70.84  673.27   70.29  673.92   70.28
  726.65   70.11  914.95      70  918.16   70.04  933.12   70.61  964.93   70.28
 1039.66      70 1071.76      70 1089.87   70.14 1190.63    70.1 1275.72    70.5
  1381.5    70.5  1401.9    69.8 1409.14   69.65 1422.37    69.6 1455.72   69.99
#Mann= 3 , 0 , 0
       0    .035       0  451.75    .018       0  533.81    .035       0
Levee=-1,340.59,70.9677,-1,647.12,70.84079,	452,	451
Bank Sta=451.75,533.81
XS Rating Curve= 0 ,0
Exp/Cntr=0.3,0.1

Type RM Length L Ch R = 1 ,6824.823,131.59,94.46,57.33
XS GIS Cut Line= 6
    1077850.8161    1572232.1172    1077906.1448    1572554.4187
    1077914.0826    1572610.7491     1077924.109    1572692.1077
    1077943.7248     1572852.662     1077993.903    1573633.3534
#Sta/Elev= 27
       0   70.25  159.44      71  235.22    71.5  341.95    71.5  372.44   69.32
   383.9   69.32  384.65   69.32  405.23   67.84  444.99   67.84  465.88   69.32
  582.12   69.31  603.17   70.81  627.63    70.8  629.35   70.24  629.69   70.23
  706.34   70.01  876.63      70  897.14    70.5 1031.73      70 1141.79      70
 1215.01   70.31 1242.65    70.5 1353.36    70.5  1360.6   70.41 1372.04      70
 1398.14      70 1409.93   70.15
#Mann= 3 , 0 , 0
       0    .035       0   383.9    .018       0  465.88    .035       0
Levee=-1,351.45,70.82193,-1,603.18,70.8055,	452,	451
Bank Sta=383.9,465.88
XS Rating Curve= 0 ,0
Exp/Cntr=0.3,0.1

Type RM Length L Ch R = 1 ,6730.362,79.99,110.99,142
XS GIS Cut Line= 6
    1077700.1091    1572245.6639    1077774.2871    1572583.9064
    1077790.7026    1572674.0781    1077886.8148    1572731.9604
    1077901.6162    1572740.9649    1077953.2629      1573641.82
#Sta/Elev= 28
       0      70  140.82      71  183.49    71.5  261.92    71.5  316.27   71.05
  369.58   70.71  391.74   69.18  467.69    69.2  468.57    69.2  488.81   67.76
  529.02   67.75  550.13   69.25  640.79   69.27  662.05   70.76  686.75   70.76
  688.56   70.16  744.64      70  963.13      70  981.52   70.21  1001.4   70.21
 1057.27      70 1230.67      70 1285.03   70.38 1319.17    70.5 1434.49    70.5
 1441.04   70.41  1451.4    70.5 1469.79    70.5
#Mann= 3 , 0 , 0
       0    .035       0  467.69    .018       0  550.13    .035       0
Levee=-1,370.74,70.6739,-1,662.07,70.76231,	452,	451
Bank Sta=467.69,550.13
XS Rating Curve= 0 ,0
Exp/Cntr=0.3,0.1

Type RM Length L Ch R = 1 ,6619.369,75.69,110.63,145.57
XS GIS Cut Line= 4
     1077636.609    1572260.0573    1077740.8731    1572639.9945
    1077809.3023    1572885.2722    1077905.0028    1573661.2934
#Sta/Elev= 22
       0      70   86.31   70.51   135.2      71  143.89      71  180.33    71.3
  277.49   71.26  358.27   70.63     373   70.63  393.98   69.13  512.11   69.13
  533.12   67.65  573.12   67.65  594.11   69.13   603.2   69.13   624.2   70.63
   648.6   70.63  650.08   70.14  715.19      70 1183.83      70 1277.34   70.41
 1326.95    70.5 1430.53    70.5
#Mann= 3 , 0 , 0
       0    .035       0  512.11    .018       0  594.11    .035       0
Levee=-1,373.04,70.6272,-1,624.23,70.62787,	452,	451
Bank Sta=512.11,594.11
XS Rating Curve= 0 ,0
Exp/Cntr=0.3,0.1

Type RM Length L Ch R = 1 ,6508.738,137.26,95.23,53.18
XS GIS Cut Line= 6
    1077584.9622     1572271.064    1077696.0224    1572605.9842
    1077725.5092    1572696.9381    1077659.7331    1572797.3003
    1077647.6157    1572818.8584    1077849.1227    1573670.6068
#Sta/Elev= 19
       0   69.95   99.18   70.52  170.27   71.02  196.52   71.12  306.69   71.01
  377.18   70.59  398.18   69.09  486.46   69.05  507.46   67.55  547.46   67.55
  567.62   68.99  568.46   68.99   662.1   68.95  683.28   70.45     851      70
 1302.36      70 1363.21   70.13 1431.56    70.5 1468.45    70.5
#Mann= 3 , 0 , 0
       0    .035       0  486.46    .018       0  568.46    .035       0
Levee=-1,377.26,70.58814,-1,683.35,70.45036,	452,	451
Bank Sta=486.46,568.46
XS Rating Curve= 0 ,0
Exp/Cntr=0.3,0.1