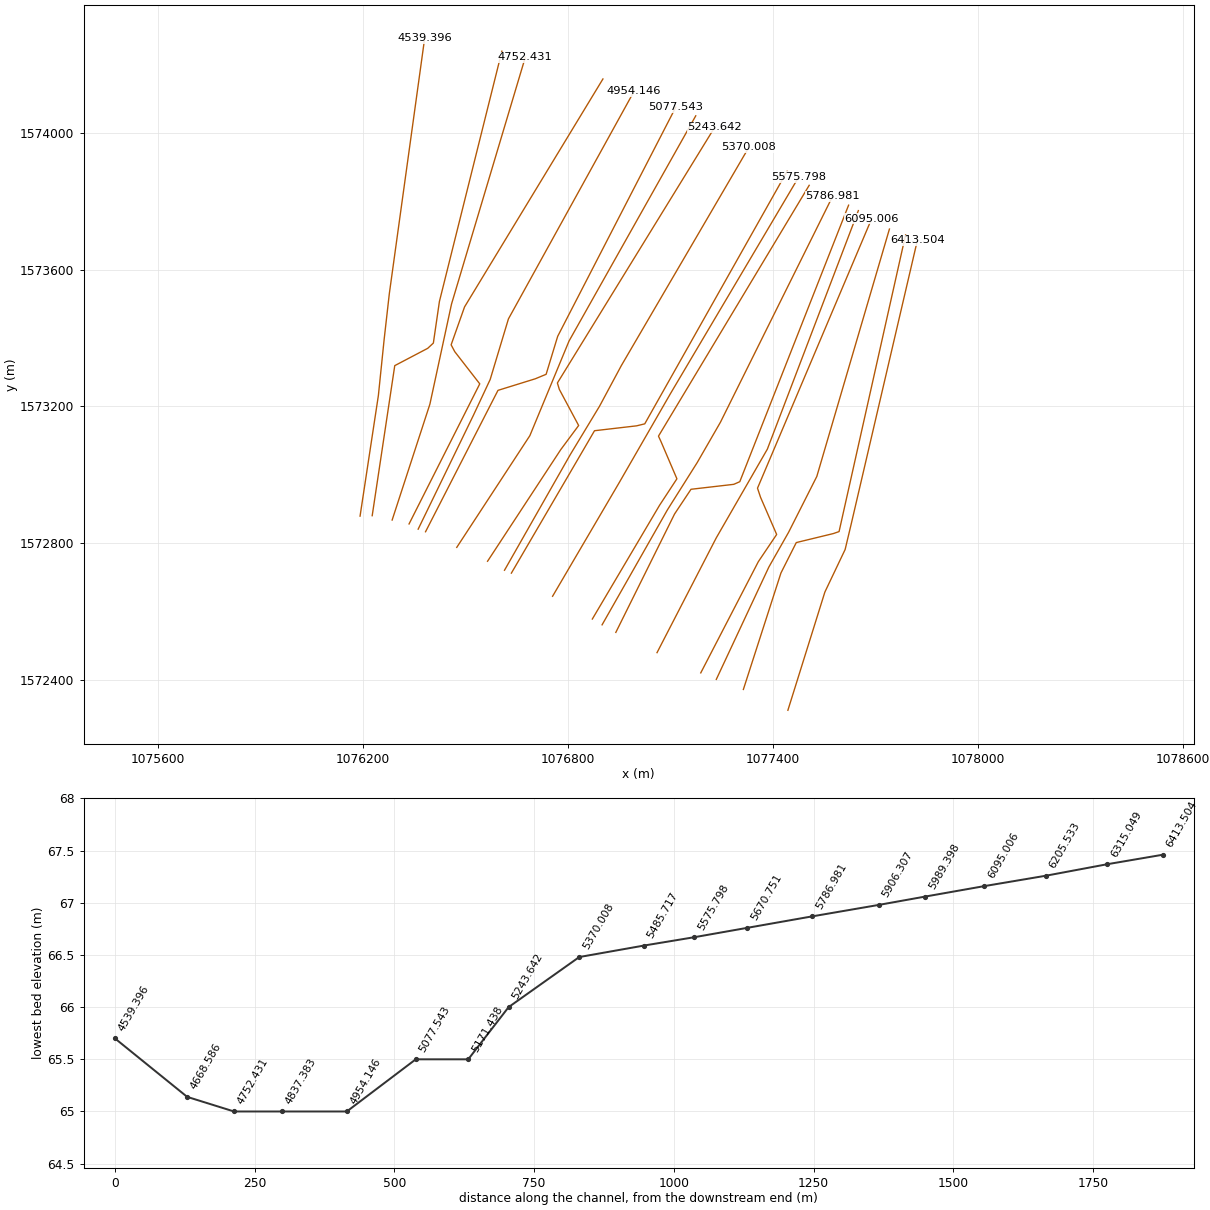
HEC-RAS study HECRAS_v2.prj: HECRAS_v2

--- HECRAS_v2.g02 (geometry) --- (continued)

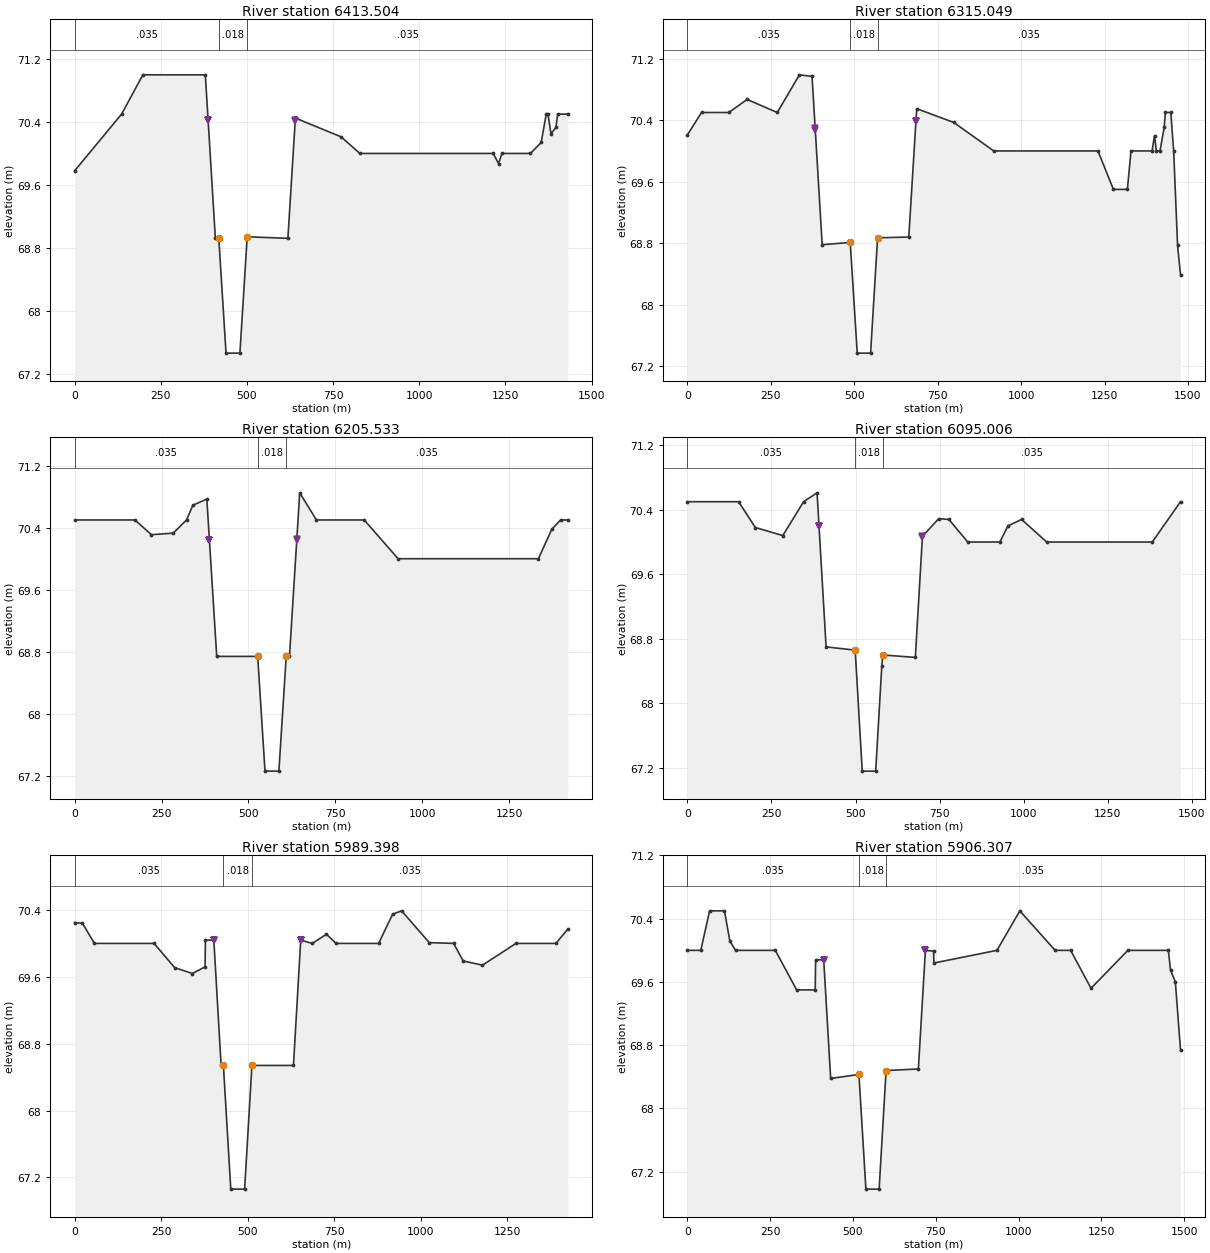
Type RM Length L Ch R = 1 ,6413.504,134.85,98.46,62.09
XS GIS Cut Line= 5
    1077443.5686    1572310.0107    1077551.8597    1572656.1842
     1077611.188    1572780.7703    1077628.1423    1572851.8785
     1077822.876    1573686.6935
#Sta/Elev= 24
       0   69.78  136.03    70.5  197.96      71  379.14      71  408.15   68.93
  418.07   68.93  439.24   67.46  479.53   67.46  500.71   68.94  618.79   68.92
  640.57   70.45  773.68   70.21  827.62      70 1214.78      70 1230.26   69.87
 1239.88      70 1322.84      70 1353.98   70.14 1368.61    70.5 1373.65    70.5
 1382.39   70.25  1396.7   70.33 1401.82    70.5 1431.03    70.5
#Mann= 3 , 0 , 0
       0    .035       0  418.07    .018       0  500.71    .035       0
Levee=-1,387.18,70.42523,-1,640.1,70.4221,	452,	451
Bank Sta=418.07,500.71
XS Rating Curve= 0 ,0
Exp/Cntr=0.3,0.1

Type RM Length L Ch R = 1 ,6315.049,74.08,109.52,144.96
XS GIS Cut Line= 6
    1077313.1817    1572370.9708    1077423.2416    1572712.0683
     1077468.122    1572801.0784    1077576.7283    1572827.4692
    1077593.4289    1572833.2518    1077788.1626    1573701.9335
#Sta/Elev= 30
       0   70.21   42.21    70.5  123.98    70.5  178.76   70.67  269.18    70.5
  335.58   70.99  373.42   70.97   403.8   68.78  487.87   68.81  508.87   67.37
  548.87   67.37  569.87   68.87  663.35   68.88  687.15   70.55  798.33   70.37
  917.92      70 1230.29      70 1276.63    69.5 1318.59    69.5 1329.36      70
  1392.6      70 1399.85    70.2 1405.43      70 1416.39      70 1428.89   70.31
 1432.59    70.5 1448.72    70.5 1457.27      70 1469.02   68.77 1477.78   68.39
#Mann= 3 , 0 , 0
       0    .035       0  487.87    .018       0  569.87    .035       0
Levee=-1,382.82,70.27781,-1,684.77,70.3833,	452,	451
Bank Sta=487.87,569.87
XS Rating Curve= 0 ,0
Exp/Cntr=0.3,0.1

Type RM Length L Ch R = 1 ,6205.533,74.56,110.53,146.5
XS GIS Cut Line= 5
    1077233.9476    1572400.4631    1077387.8418    1572729.4454
    1077445.6147    1572831.2056    1077528.2412    1572994.6647
    1077740.8903    1573719.1491
#Sta/Elev= 21
       0    70.5   173.1    70.5  220.77   70.31  283.52   70.33   321.7    70.5
  340.03   70.69  380.17   70.77  408.61   68.74  526.43   68.74  547.49   67.26
  587.46   67.26   608.5   68.74   617.9   68.74  647.39   70.85  695.43    70.5
  832.92    70.5   930.4      70 1333.93      70 1372.57   70.38 1397.81    70.5
 1418.42    70.5
#Mann= 3 , 0 , 0
       0    .035       0  526.43    .018       0   608.5    .035       0
Levee=-1,387.62,70.23576,-1,638.97,70.24936,	452,	451
Bank Sta=526.43,608.5
XS Rating Curve= 0 ,0
Exp/Cntr=0.3,0.1

Type RM Length L Ch R = 1 ,6095.006,143.8,105.61,67.44
XS GIS Cut Line= 6
    1077188.4392    1572419.5131     1077357.076    1572745.2403
    1077410.6896    1572824.8556    1077363.6318    1572933.3258
    1077354.5979    1572960.3226    1077689.0319    1573749.8408
#Sta/Elev= 23
       0    70.5  151.99    70.5  202.07   70.18  283.61   70.08   345.5    70.5
  385.59   70.61  412.47    68.7  499.01   68.66  520.01   67.16  560.01   67.16
  578.16   68.46  581.01    68.6  677.97   68.57  699.13   70.07  747.43   70.29
  777.84   70.28  833.95      70  929.52      70  953.49    70.2  994.02   70.28
  1068.9      70 1382.95      70 1466.91    70.5
#Mann= 3 , 0 , 0
       0    .035       0  499.01    .018       0  581.01    .035       0
Levee=-1,391.31,70.20357,-1,699.13,70.06611,	452,	451
Bank Sta=499.01,581.01
XS Rating Curve= 0 ,0
Exp/Cntr=0.3,0.1

Type RM Length L Ch R = 1 ,5989.398,121.37,83.09,44.79
XS GIS Cut Line= 4
    1077060.3806    1572478.7799    1077233.6889    1572814.6025
    1077383.3932    1573074.5806    1077649.8734    1573773.1242
#Sta/Elev= 29
       0   70.25   22.52   70.24   57.17      70  229.63      70  289.08   69.71
  340.42   69.64  376.94   69.72  377.91   70.04  402.31   70.04  423.31   68.54
  429.95   68.54  451.32   67.06  491.32   67.06  512.44   68.54  632.51   68.54
  653.51   70.04  686.79      70  728.05   70.11  755.84      70  878.72      70
  919.33   70.35  945.31   70.39 1025.05   70.01 1095.71      70 1123.34   69.79
 1179.03   69.74 1275.93      70 1391.12      70 1425.55   70.17
#Mann= 3 , 0 , 0
       0    .035       0  429.95    .018       0  512.44    .035       0
Levee=-1,402.31,70.04148,-1,653.5,70.04148,	452,	451
Bank Sta=429.95,512.44
XS Rating Curve= 0 ,0
Exp/Cntr=0.3,0.1

Type RM Length L Ch R = 1 ,5906.307,81.06,119.33,157.59
XS GIS Cut Line= 6
    1076939.7304    1572538.0467    1077111.7443    1572884.8224
    1077159.8641    1572957.1476    1077285.0474    1572971.6098
    1077302.7394    1572979.3726    1077621.2984    1573788.9992
#Sta/Elev= 30
       0      70   40.27      70   66.86    70.5  111.76    70.5  127.91   70.12
  145.25      70   265.4      70  329.76    69.5  385.96    69.5  387.09   69.88
  411.55   69.88  432.59   68.38  517.98   68.43  538.98   66.98  578.98   66.98
  599.98   68.48  697.51    68.5  718.74      70   743.4   69.99  744.57   69.84
  934.84      70 1003.96    70.5 1110.66      70 1157.53      70 1219.02   69.52
 1330.28      70  1452.6      70 1459.13   69.75 1473.79    69.6 1489.34   68.74
#Mann= 3 , 0 , 0
       0    .035       0  517.98    .018       0  599.98    .035       0
Levee=-1,411.54,69.87965,-1,718.73,69.99842,	452,	451
Bank Sta=517.98,599.98
XS Rating Curve= 0 ,0
Exp/Cntr=0.3,0.1

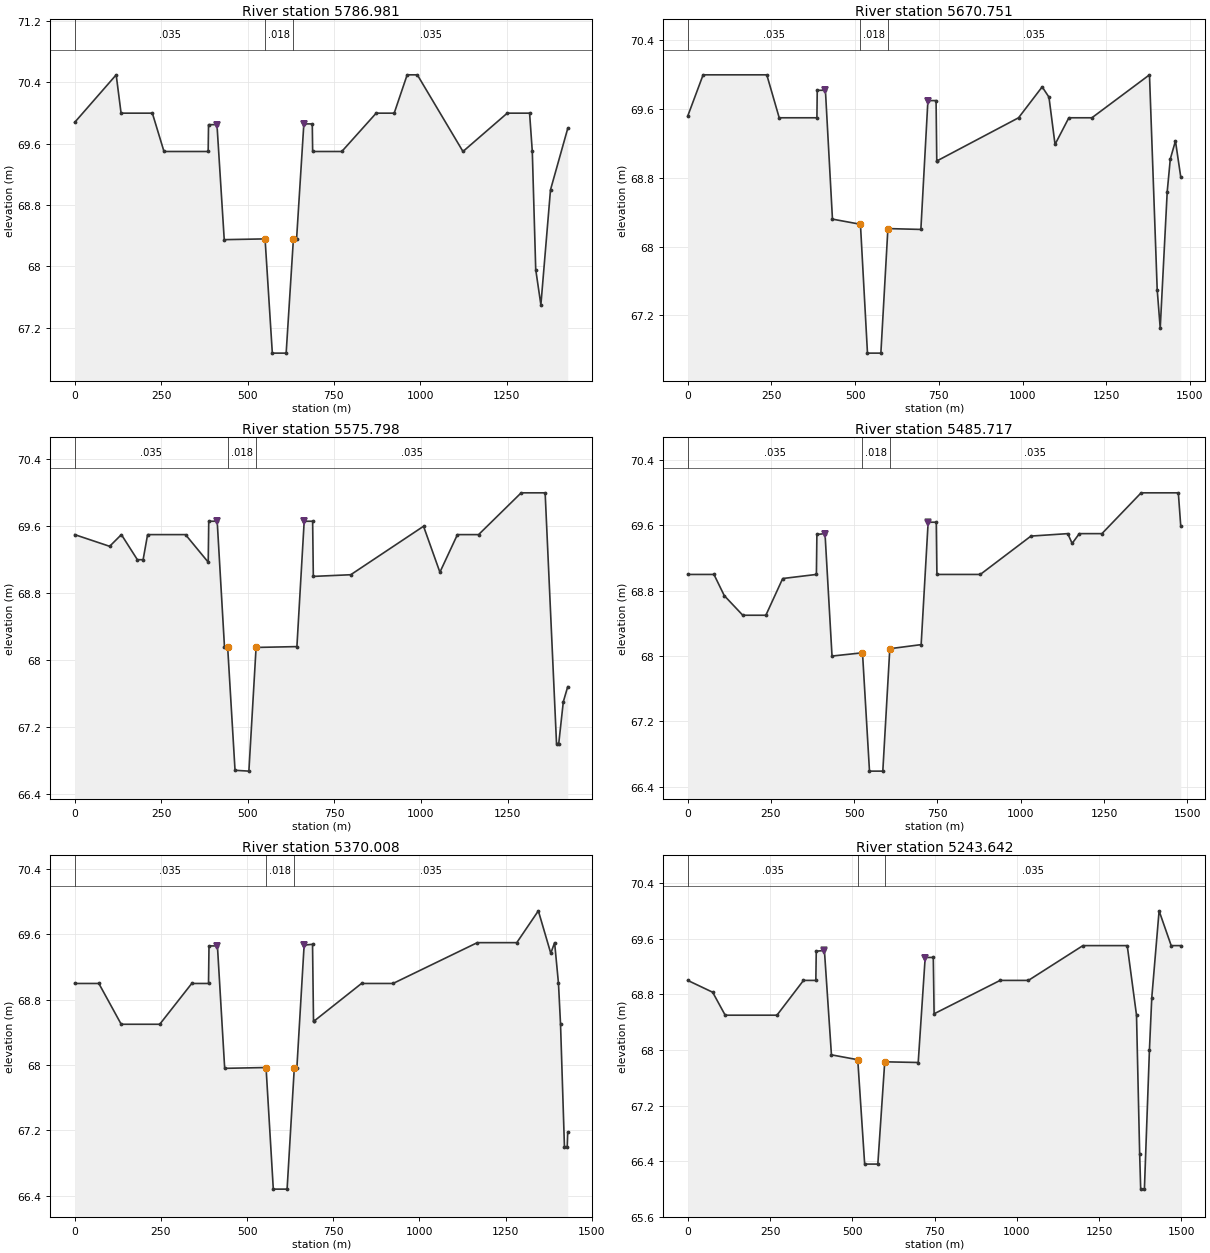
Type RM Length L Ch R = 1 ,5786.981,78.24,116.23,154.22
XS GIS Cut Line= 5
    1076899.5136    1572560.2718    1077090.7895    1572896.8889
    1077177.9757    1573035.2595     1077246.132    1573153.6204
    1077574.7316    1573815.4576
#Sta/Elev= 30
       0   69.88  120.01    70.5  134.18      70  224.66      70  258.32    69.5
  386.12    69.5  387.17   69.85  411.59   69.85   432.6   68.35  550.71   68.36
  571.73   66.87  611.73   66.87  632.72   68.36   641.9   68.36   662.9   69.86
   687.3   69.86  688.37    69.5  772.67    69.5   872.1      70  924.27      70
  961.77    70.5  991.19    70.5 1123.24    69.5 1251.27      70 1315.92      70
 1323.77    69.5 1333.68   67.96  1348.6    67.5 1376.42      69 1426.22    69.8
#Mann= 3 , 0 , 0
       0    .035       0  550.71    .018       0  632.72    .035       0
Levee=-1,411.59,69.85081,-1,662.9,69.85725,	452,	451
Bank Sta=550.71,632.72
XS Rating Curve= 0 ,0
Exp/Cntr=0.3,0.1

Type RM Length L Ch R = 1 ,5670.751,132.94,94.95,56.97
XS GIS Cut Line= 6
    1076870.9386    1572577.2051     1077067.716    1572910.1754
    1077118.5891    1572987.8393     1077072.109    1573096.5388
    1077064.6139    1573112.7229    1077505.9398    1573847.2077
#Sta/Elev= 30
       0   69.52   45.93      70  236.11      70   273.2    69.5  385.81    69.5
  386.77   69.82  411.21   69.82  432.24   68.32  515.83   68.26  536.83   66.76
  576.83   66.76  597.83   68.21   696.3    68.2  717.31    69.7  741.71    69.7
  743.77      69  745.45      69  988.08    69.5 1058.63   69.86 1078.89   69.74
 1097.03   69.19 1138.25    69.5 1207.16    69.5 1379.11      70 1402.13    67.5
 1411.17   67.05 1432.08   68.64  1441.3   69.02 1456.66   69.23 1472.54   68.81
#Mann= 3 , 0 , 0
       0    .035       0  515.83    .018       0  597.83    .035       0
Levee=-1,411.21,69.82031,-1,717.31,69.70021,	452,	451
Bank Sta=515.83,597.83
XS Rating Curve= 0 ,0
Exp/Cntr=0.3,0.1

Type RM Length L Ch R = 1 ,5575.798,128.33,90.08,51.83
XS GIS Cut Line= 4
    1076754.5217    1572643.8803    1076950.2991    1572977.7881
    1077100.0034    1573237.7662    1077475.2481    1573871.5494
#Sta/Elev= 30
       0    69.5  100.91   69.36  134.82    69.5     181    69.2  197.57    69.2
   210.5    69.5  319.97    69.5  385.58   69.17  387.07   69.66  411.47   69.66
  432.47   68.16  441.62   68.16  462.99   66.68     503   66.67  523.77   68.15
  641.67   68.16  662.67   69.66  687.07   69.66  689.05      69  797.09   69.02
 1007.31    69.6 1054.55   69.05 1105.13    69.5 1166.26    69.5 1289.24      70
 1358.44      70 1391.28      67 1397.71      67 1410.88    67.5 1423.61   67.68
#Mann= 3 , 0 , 0
       0    .035       0  441.62    .018       0  523.77    .035       0
Levee=-1,411.47,69.66111,-1,662.67,69.66111,	452,	451
Bank Sta=441.62,523.77
XS Rating Curve= 0 ,0
Exp/Cntr=0.3,0.1

Type RM Length L Ch R = 1 ,5485.717,76.24,115.71,155.18
XS GIS Cut Line= 6
    1076633.8714    1572711.6137    1076829.4693    1573046.4807
    1076877.2886    1573128.5979    1077000.4639    1573142.8945
    1077024.3972    1573148.7063    1077441.3814    1573888.4828
#Sta/Elev= 27
       0      69   78.73      69  109.78   68.74  165.32    68.5  234.63    68.5
  285.19   68.95  386.39      69  387.88   69.49  412.29    69.5  433.31      68
  524.83   68.04  545.84   66.59  585.84   66.59  606.84   68.09  700.97   68.14
  721.98   69.64  746.38   69.64   748.3      69  878.64      69 1030.75   69.47
 1141.26    69.5 1154.45   69.38 1175.95    69.5 1243.88    69.5 1361.64      70
 1473.37      70 1480.66   69.59
#Mann= 3 , 0 , 0
       0    .035       0  524.83    .018       0  606.84    .035       0
Levee=-1,412.22,69.49551,-1,721.97,69.6356,	452,	451
Bank Sta=524.83,606.84
XS Rating Curve= 0 ,0
Exp/Cntr=0.3,0.1

Type RM Length L Ch R = 1 ,5370.008,86.03,126.37,166.7
XS GIS Cut Line= 5
     1076613.763    1572720.0804    1076806.3819    1573058.7514
    1076892.0198    1573200.3694    1076955.7618    1573319.1616
    1077329.1978    1573958.3329
#Sta/Elev= 30
       0      69   70.07      69  134.95    68.5  246.67    68.5  339.58      69
  388.22      69   389.6   69.46  414.06   69.46   435.1   67.96  555.11   67.97
  576.15   66.48  616.17   66.48  637.12   67.97  644.56   67.97  665.56   69.47
  689.96   69.48  692.77   68.54  694.69   68.54  832.05      69  923.53      69
 1167.81    69.5 1282.43    69.5    1345   69.89 1381.04   69.37 1392.19    69.5
  1403.4      69 1409.36    68.5 1420.71      67 1428.75      67 1430.19   67.18
#Mann= 3 , 0 , 0
       0    .035       0  555.11    .018       0  637.12    .035       0
Levee=-1,414.06,69.46284,-1,665.53,69.47281,	452,	451
Bank Sta=555.11,637.12
XS Rating Curve= 0 ,0
Exp/Cntr=0.3,0.1

Type RM Length L Ch R = 1 ,5243.642,108.46,72.2,35.89
XS GIS Cut Line= 6
     1076564.143    1572746.4171    1076778.2474    1573072.9603
    1076830.8435    1573143.9279     1076774.338    1573249.5473
    1076768.6134    1573268.3881    1077229.6243    1574017.6896
#Sta/Elev= 30
       0      69   75.71   68.83  113.77    68.5  271.05    68.5  351.71      69
  389.21      69  390.48   69.42  415.29   69.43  436.62   67.93  516.59   67.86
  537.59   66.36  577.59   66.36  598.59   67.83  700.27   67.82  721.48   69.33
  746.11   69.33  748.58   68.52  949.16      69 1035.06      69 1200.76    69.5
  1335.4    69.5 1363.58    68.5 1373.19    66.5 1376.29      66 1387.57      66
 1402.85      68 1409.95   68.75 1432.21      70 1468.98    69.5 1498.05    69.5
#Mann= 3 , 0 , 0
       0    .035       0  516.59    .018       0  598.59    .035       0
Levee=-1,415.26,69.4268,-1,721.41,69.32336,	452,	451
Bank Sta=516.59,598.59
XS Rating Curve= 0 ,0
Exp/Cntr=0.3,0.1

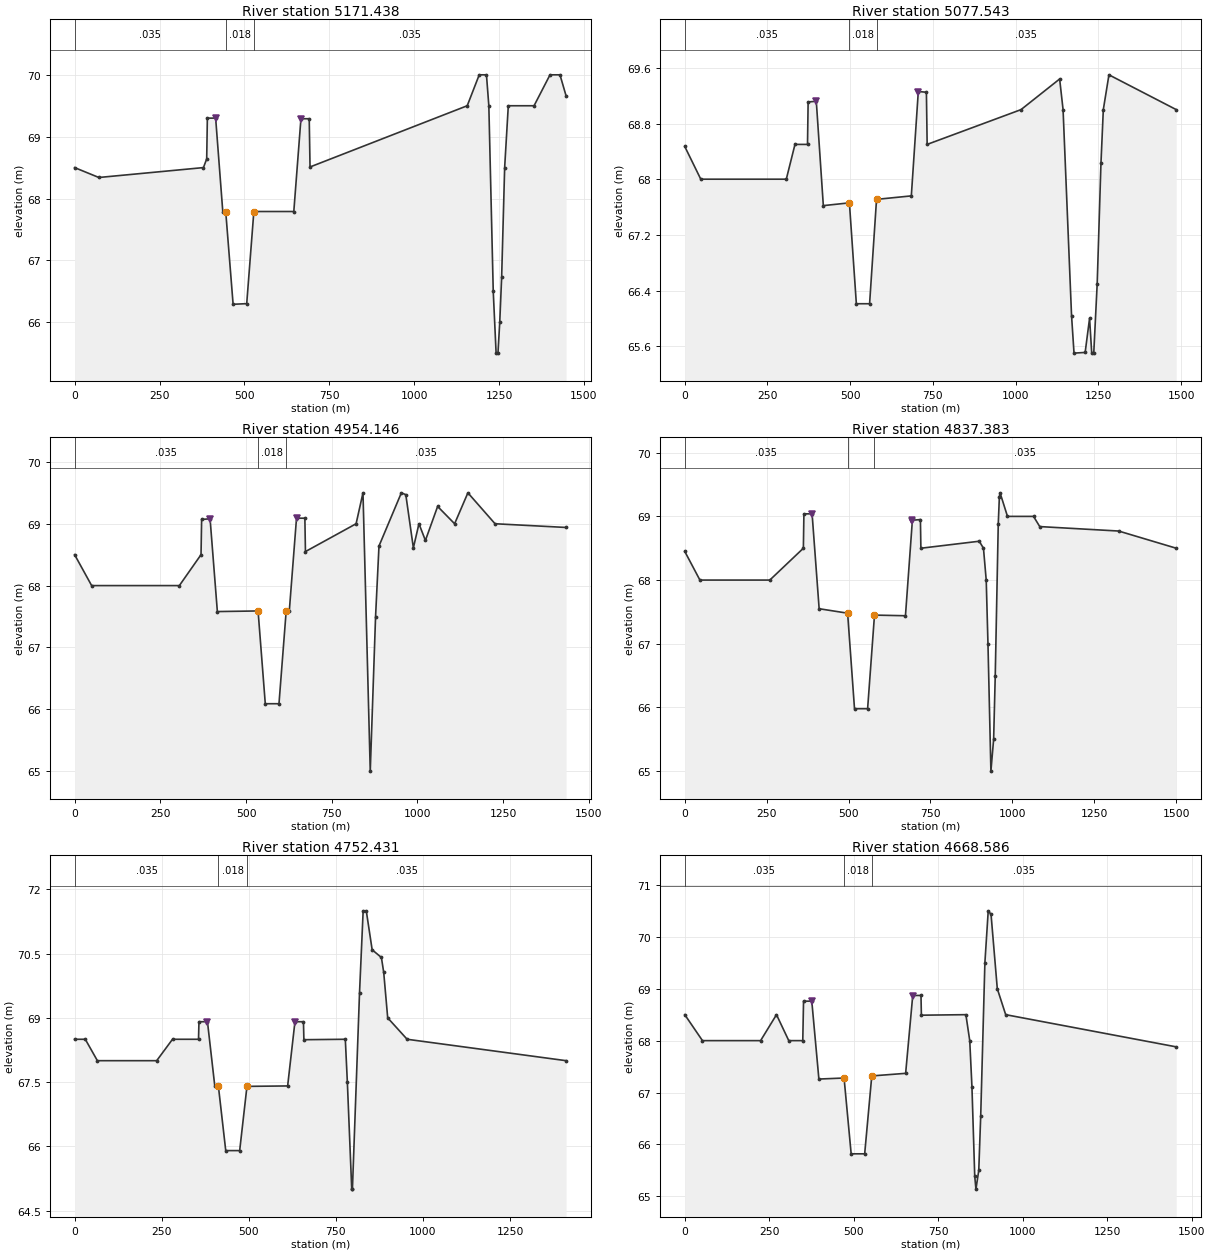
Type RM Length L Ch R = 1 ,5171.438,129.85,93.89,58
XS GIS Cut Line= 4
    1076473.9728    1572787.0572     1076687.982     1573114.152
    1076802.7586    1573391.3524    1077173.7442    1574050.7097
#Sta/Elev= 30
       0    68.5   71.39   68.34  379.43    68.5     389   68.64  390.96    69.3
  415.36    69.3  436.36   67.79  445.03   67.79  466.78   66.29  506.85    66.3
  527.88   67.79  645.56   67.79  666.56   69.29  690.96   69.29  693.32   68.51
  1156.3    69.5 1191.62      70 1212.95      70 1219.94    69.5 1232.91    66.5
 1241.35    65.5 1246.81    65.5 1252.08      66 1257.68   66.73 1266.53    68.5
 1277.26    69.5 1353.11    69.5 1400.12      70 1429.45      70 1447.47   69.66
#Mann= 3 , 0 , 0
       0    .035       0  445.03    .018       0  527.88    .035       0
Levee=-1,415.32,69.29516,-1,666.51,69.28971,	452,	451
Bank Sta=445.03,527.88
XS Rating Curve= 0 ,0
Exp/Cntr=0.3,0.1

Type RM Length L Ch R = 1 ,5077.543,83.32,123.4,163.47
XS GIS Cut Line= 6
    1076382.5326    1572832.7773     1076594.623    1573246.7981
       1076703.8    1573280.6628    1076735.5933    1573293.7882
    1076769.4509    1573405.0022    1077115.3241    1574076.1098
#Sta/Elev= 30
       0   68.47   48.38      68  306.81      68  333.04    68.5  370.91    68.5
  372.77   69.11  397.46   69.12   418.7   67.62   497.5   67.66   518.5   66.21
   558.5   66.21   579.5   67.71  684.61   67.76  705.68   69.26  730.17   69.25
  732.43    68.5  1016.1      69 1132.79   69.44 1143.16      69 1168.76   66.04
 1176.23    65.5 1209.88   65.51 1223.25      66 1229.74    65.5 1235.88    65.5
 1246.28    66.5 1257.66   68.23 1264.77      69 1281.78    69.5 1485.14      69
#Mann= 3 , 0 , 0
       0    .035       0   497.5    .018       0   579.5    .035       0
Levee=-1,397.43,69.11753,-1,705.67,69.25622,	452,	451
Bank Sta=497.5,579.5
XS Rating Curve= 0 ,0
Exp/Cntr=0.3,0.1

Type RM Length L Ch R = 1 ,4954.146,77.69,116.76,155.84
XS GIS Cut Line= 5
    1076360.9426    1572840.3973    1076522.6273    1573173.6284
     1076571.763    1573278.5482     1076625.239    1573456.0351
    1076993.4038    1574123.0998
#Sta/Elev= 30
       0    68.5   49.67      68  305.51      68  368.72    68.5  370.46   69.07
  395.13   69.08  416.36   67.58  535.11   67.59  556.13   66.09   596.1   66.09
  617.11   67.59  626.21   67.59  647.21   69.09  671.61   69.09  673.27   68.55
  821.02      69  841.11    69.5  862.31      65  877.82    67.5  887.79   68.64
  953.05    69.5  966.01   69.47  988.07   68.61 1004.36      69  1023.2   68.73
 1058.81   69.28 1108.36      69  1147.1    69.5 1226.28      69 1433.53   68.94
#Mann= 3 , 0 , 0
       0    .035       0  535.11    .018       0  617.11    .035       0
Levee=-1,395.07,69.07672,-1,647.21,69.09056,	452,	451
Bank Sta=535.11,617.11
XS Rating Curve= 0 ,0
Exp/Cntr=0.3,0.1

Type RM Length L Ch R = 1 ,4837.383,120.75,84.95,49.15
XS GIS Cut Line= 6
    1076334.2725    1572855.6373    1076541.2829    1573265.8481
    1076467.9322    1573360.2821    1076457.4628    1573380.1484
    1076496.7003    1573491.0702    1076901.9637    1574158.6599
#Sta/Elev= 30
       0   68.45   46.23      68  259.58      68  362.04    68.5  363.67   69.04
  388.67   69.04  410.18   67.55  497.12   67.48  518.12   65.98  558.12   65.98
  579.12   67.45  673.65   67.44  694.77   68.94  719.31   68.95  720.72    68.5
  898.87   68.61  911.77    68.5  920.16      68   925.5      67  934.48      65
  942.79    65.5  947.72    66.5  956.91   68.88  960.34   69.31  962.43   69.37
  985.08      69 1064.59      69 1083.55   68.84 1324.44   68.77  1500.2    68.5
#Mann= 3 , 0 , 0
       0    .035       0  497.12    .018       0  579.12    .035       0
Levee=-1,388.6,69.04321,-1,694.69,68.93905,	452,	451
Bank Sta=497.12,579.12
XS Rating Curve= 0 ,0
Exp/Cntr=0.3,0.1

Type RM Length L Ch R = 1 ,4752.431,119.7,83.84,48
XS GIS Cut Line= 4
    1076284.7424    1572867.0673    1076395.3011    1573206.4879
    1076458.6237    1573499.6809    1076674.6332      1574222.16
#Sta/Elev= 30
       0    68.5   30.64    68.5   65.37      68  235.65      68  281.05    68.5
  355.73    68.5     357   68.91   381.4   68.91   402.4   67.41  412.68   67.41
  433.88    65.9  473.88    65.9   494.8    67.4  611.59   67.41  632.59   68.91
  656.99   68.91  658.24   68.49  777.15    68.5  783.01    67.5  795.58      65
  797.57      65  817.95   69.58   828.4    71.5  837.36    71.5  854.22   70.59
   880.8   70.41  887.44   70.06  898.85      69  954.63    68.5 1411.01      68
#Mann= 3 , 0 , 0
       0    .035       0  412.68    .018       0   494.8    .035       0
Levee=-1,381.33,68.90533,-1,632.53,68.90067,	452,	451
Bank Sta=412.68,494.8
XS Rating Curve= 0 ,0
Exp/Cntr=0.3,0.1

Type RM Length L Ch R = 1 ,4668.586,89.24,129.19,169.14
XS GIS Cut Line= 6
    1076226.3223    1572879.7674    1076292.3624    1573319.1882
    1076388.8975    1573369.8806    1076405.3927    1573385.2284
    1076423.1416    1573506.9892    1076606.0531    1574239.9401
#Sta/Elev= 30
       0    68.5   52.38      68  224.41      68  271.43    68.5  307.76      68
  349.22      68  351.49   68.76  375.89   68.76   396.9   67.26  471.41   67.28
  492.41   65.82  532.41   65.82  553.41   67.32  653.62   67.37  674.64   68.87
  699.07   68.87   700.2   68.49   831.9    68.5  843.31      68  849.85   67.11
  858.08   65.39  861.66   65.14  870.03    65.5  875.78   66.55  888.15    69.5
  898.03    70.5  906.37   70.43  924.85      69   949.7    68.5 1454.42   67.88
#Mann= 3 , 0 , 0
       0    .035       0  471.41    .018       0  553.41    .035       0
Levee=-1,375.89,68.75673,-1,674.56,68.86214,	452,	451
Bank Sta=471.41,553.41
XS Rating Curve= 0 ,0
Exp/Cntr=0.3,0.1

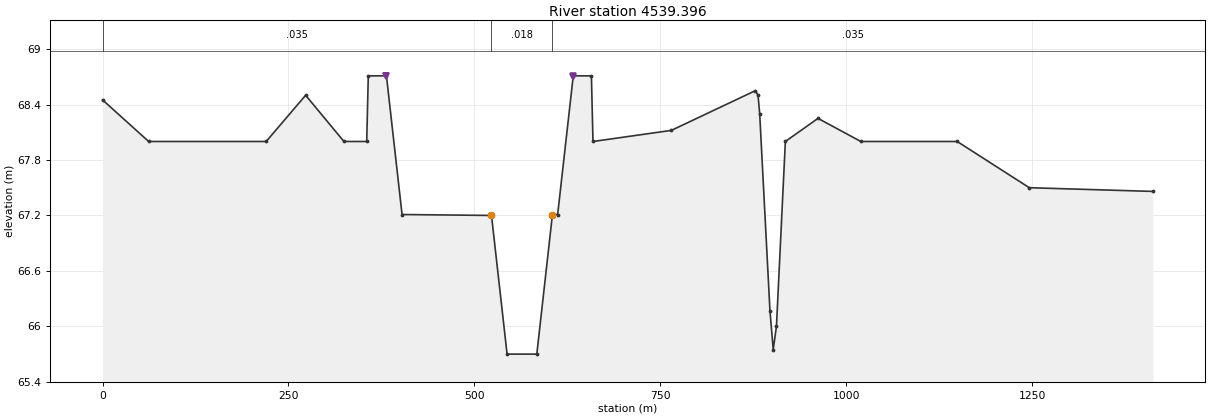
Type RM Length L Ch R = 1 ,4539.396,86.71,126.39,166.08
XS GIS Cut Line= 5
    1076190.7622    1572878.4974    1076244.4195    1573231.7166
    1076261.3718    1573396.5976    1076276.4864    1573530.0372
    1076379.9926    1574278.0402
#Sta/Elev= 30
       0   68.45   62.01      68  220.03      68   273.1    68.5   324.6      68
  355.22      68  357.35   68.71  381.76   68.71  402.76   67.21  523.02    67.2
  543.99    65.7  583.97    65.7  604.98   67.21  611.99   67.21  632.98   68.71
  657.38   68.71  659.51      68  764.89   68.12   877.9   68.55  881.45    68.5
  883.68    68.3  897.48   66.17  901.88   65.75  906.23      66   918.2      68
  962.09   68.25 1019.72      68  1149.3      68 1246.26    67.5 1412.45   67.46
#Mann= 3 , 0 , 0
       0    .035       0  523.02    .018       0  604.98    .035       0
Levee=-1,381.76,68.71023,-1,632.92,68.70223,	452,	451
Bank Sta=523.02,604.98
XS Rating Curve= 0 ,0
Exp/Cntr=0.3,0.1