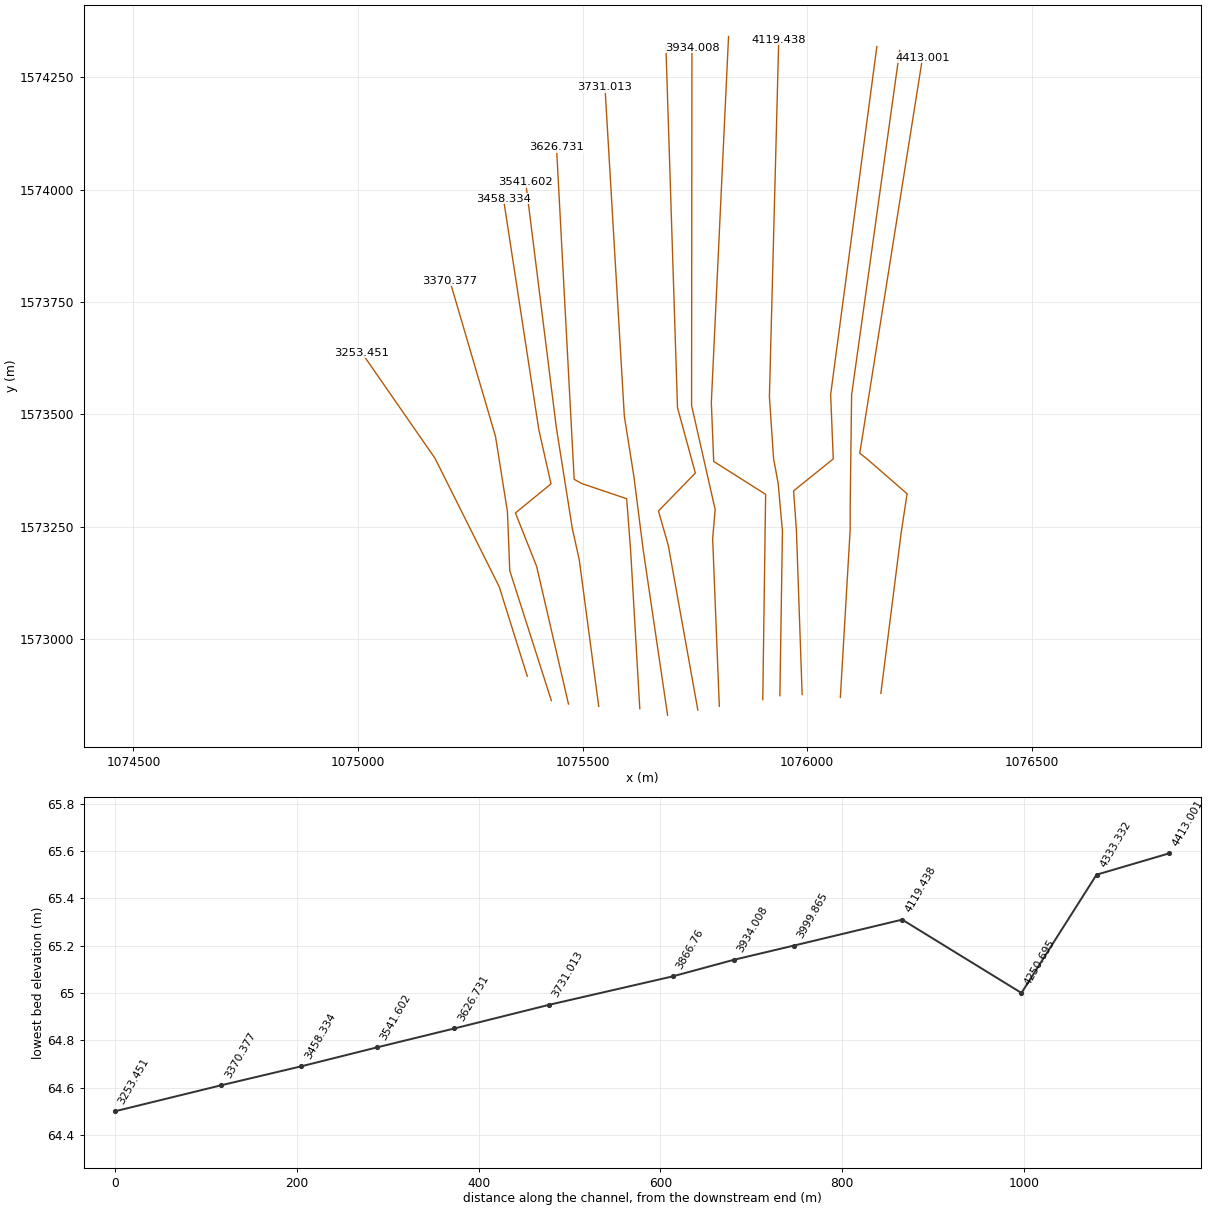
HEC-RAS study HECRAS_v2.prj: HECRAS_v2

--- HECRAS_v2.g02 (geometry) --- (continued)

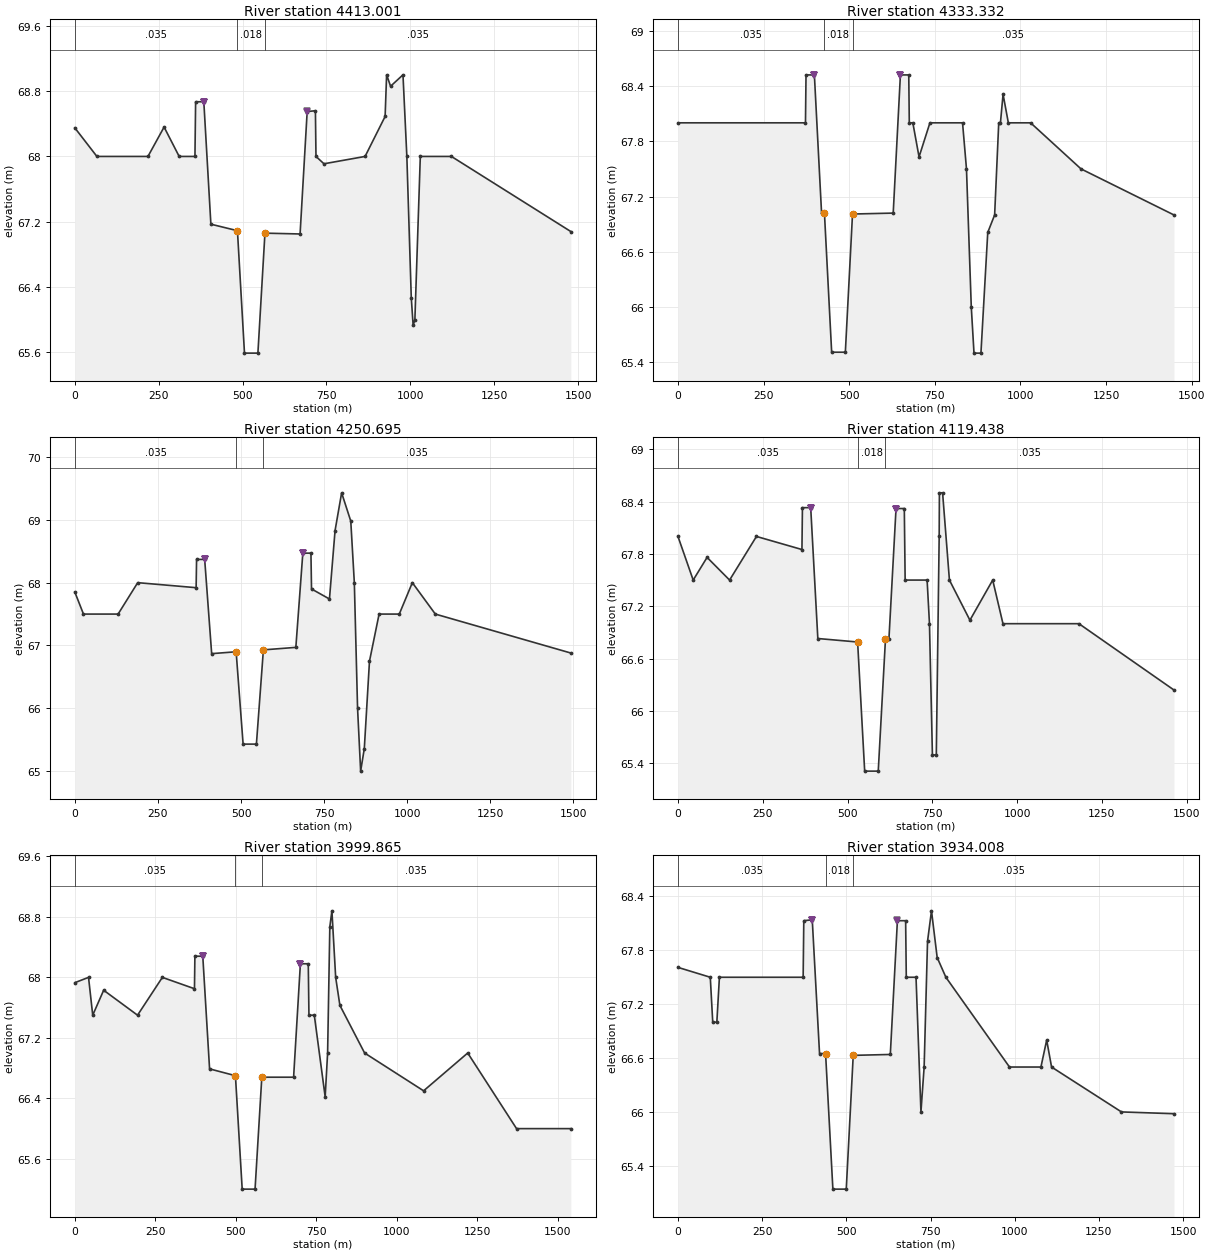
Type RM Length L Ch R = 1 ,4413.001,115.26,79.67,44.08
XS GIS Cut Line= 6
    1076164.0922    1572878.4974    1076209.2256     1573235.565
    1076222.5123    1573322.9982    1076133.2626    1573400.5867
    1076117.1021    1573413.1684    1076256.8024    1574293.2802
#Sta/Elev= 30
       0   68.35   65.75      68   217.9      68     266   68.36  310.94      68
  357.98      68  359.98   68.67  384.41   68.67  405.44   67.17  484.61   67.09
  505.61   65.59  545.61   65.59  566.61   67.06  671.33   67.05  692.46   68.55
  717.02   68.56   718.7      68   742.5   67.91  865.02      68  924.77   68.49
  929.22      69  941.06   68.86     978      69  989.52      68 1002.71   66.27
 1008.28   65.93 1013.48      66 1029.66      68  1122.4      68 1478.21   67.08
#Mann= 3 , 0 , 0
       0    .035       0  484.61    .018       0  566.61    .035       0
Levee=-1,384.41,68.66766,-1,692.46,68.55412,	452,	451
Bank Sta=484.61,566.61
XS Rating Curve= 0 ,0
Exp/Cntr=0.3,0.1

Type RM Length L Ch R = 1 ,4333.332,118.69,82.64,46.58
XS GIS Cut Line= 5
     1076073.922    1572869.6073    1076095.7669    1573242.7902
    1076095.8113    1573296.6783    1076098.9794    1573542.8593
    1076206.0023    1574309.7902
#Sta/Elev= 30
       0      68  372.35      68  373.92   68.52  398.33   68.52  419.33   67.02
  427.71   67.02  448.79   65.51  488.77   65.51   509.7   67.01  628.54   67.02
  649.54   68.52  673.94   68.52   675.5      68  685.83      68  703.97   67.63
  735.73      68  830.98      68  842.46    67.5   856.5      66  864.43    65.5
  884.68    65.5   904.6   66.81   924.7      67  936.67      68  941.65      68
  949.31   68.31  964.73      68 1029.76      68 1176.82    67.5 1448.27      67
#Mann= 3 , 0 , 0
       0    .035       0  427.71    .018       0   509.7    .035       0
Levee=-1,398.26,68.52103,-1,649.51,68.51373,	452,	451
Bank Sta=427.71,509.7
XS Rating Curve= 0 ,0
Exp/Cntr=0.3,0.1

Type RM Length L Ch R = 1 ,4250.695,91.93,131.26,170.59
XS GIS Cut Line= 6
    1075988.8318    1572875.9574    1075976.0759    1573241.9826
    1075969.7818    1573329.3483    1076058.1338    1573400.5828
    1076052.2987    1573543.5784    1076155.2022    1574318.6802
#Sta/Elev= 30
       0   67.85   25.95    67.5  130.16    67.5  189.18      68  364.95   67.92
  366.28   68.37  390.69   68.37   411.7   66.87  485.33    66.9  506.33   65.43
  546.33   65.43  567.33   66.93  664.99   66.97     686   68.47  710.43   68.47
  712.14    67.9  766.12   67.74  783.01   68.83  802.76   69.43  830.27   68.98
  840.97      68  850.71      66  859.99      65  871.02   65.36  886.55   66.75
   915.5    67.5  976.22    67.5 1015.52      68 1084.66    67.5 1492.35   66.88
#Mann= 3 , 0 , 0
       0    .035       0  485.33    .018       0  567.33    .035       0
Levee=-1,390.63,68.36917,-1,686.03,68.46698,	452,	451
Bank Sta=485.33,567.33
XS Rating Curve= 0 ,0
Exp/Cntr=0.3,0.1

Type RM Length L Ch R = 1 ,4119.438,81.06,119.57,158.08
XS GIS Cut Line= 6
    1075939.3017    1572873.4173    1075944.9918     1573240.313
    1075935.4917    1573345.8583     1075925.201     1573401.759
    1075915.9794    1573539.0491    1075936.7617    1574333.9203
#Sta/Elev= 30
       0      68   44.88    67.5   85.85   67.76   152.2    67.5  231.42      68
  365.57   67.85  367.01   68.33  391.42   68.33  412.42   66.83  529.75   66.79
  550.55   65.31  590.57   65.31  611.84   66.82  622.02   66.82  643.02   68.32
  667.42   68.32  669.89    67.5  734.65    67.5  741.62      67  750.32   65.49
  761.78    65.5  770.24      68  770.91    68.5  780.32    68.5  800.46    67.5
  860.88   67.04  928.08    67.5  958.33      67 1182.36      67 1462.49   66.24
#Mann= 3 , 0 , 0
       0    .035       0  529.75    .018       0  611.84    .035       0
Levee=-1,391.34,68.32964,-1,642.95,68.31426,	452,	451
Bank Sta=529.75,611.84
XS Rating Curve= 0 ,0
Exp/Cntr=0.3,0.1

Type RM Length L Ch R = 1 ,3999.865,97.98,65.86,33.74
XS GIS Cut Line= 6
    1075901.2017    1572864.5273    1075907.5517    1573321.7282
    1075803.0057    1573387.9396    1075791.9814    1573394.7534
     1075786.682    1573526.0121    1075825.0015    1574340.9053
#Sta/Elev= 30
       0   67.93   42.55      68   55.58    67.5   89.53   67.83  194.85    67.5
  271.96      68  371.73   67.85  373.03   68.28  397.55   68.28  418.66   66.79
  498.99    66.7  519.99    65.2  559.99    65.2  580.99   66.68  679.75   66.68
  700.84   68.18  725.34   68.18  727.42    67.5  744.08    67.5  777.85   66.42
  785.42      67  792.32   68.67   798.8   68.88  810.47      68  823.59   67.63
  900.37      67 1083.71    66.5 1220.78      67 1372.53      66 1541.11      66
#Mann= 3 , 0 , 0
       0    .035       0  498.99    .018       0  580.99    .035       0
Levee=-1,397.48,68.2845,-1,700.83,68.17663,	452,	451
Bank Sta=498.99,580.99
XS Rating Curve= 0 ,0
Exp/Cntr=0.3,0.1

Type RM Length L Ch R = 1 ,3934.008,108.06,67.25,26.76
XS GIS Cut Line= 5
    1075804.4698    1572849.9223    1075789.6089    1573223.3002
    1075795.2326    1573287.7291    1075742.7034    1573519.6107
    1075743.5097    1574316.3519
#Sta/Elev= 30
       0   67.61   95.96    67.5  103.26      67  115.46      67  123.08    67.5
  371.76    67.5  373.67   68.13  398.79   68.14  420.41   66.65  438.35   66.65
  460.03   65.14  499.76   65.14  520.46   66.63  630.59   66.64  651.64   68.13
   676.1   68.13  678.02    67.5  706.95    67.5  721.56      66  731.03    66.5
  741.11    67.9  752.87   68.24  769.74   67.72   795.6    67.5  984.51    66.5
 1077.86    66.5 1094.95    66.8 1109.44    66.5 1316.99      66 1472.85   65.98
#Mann= 3 , 0 , 0
       0    .035       0  438.35    .018       0  520.46    .035       0
Levee=-1,398.75,68.13966,-1,651.64,68.13318,	452,	451
Bank Sta=438.35,520.46
XS Rating Curve= 0 ,0
Exp/Cntr=0.3,0.1

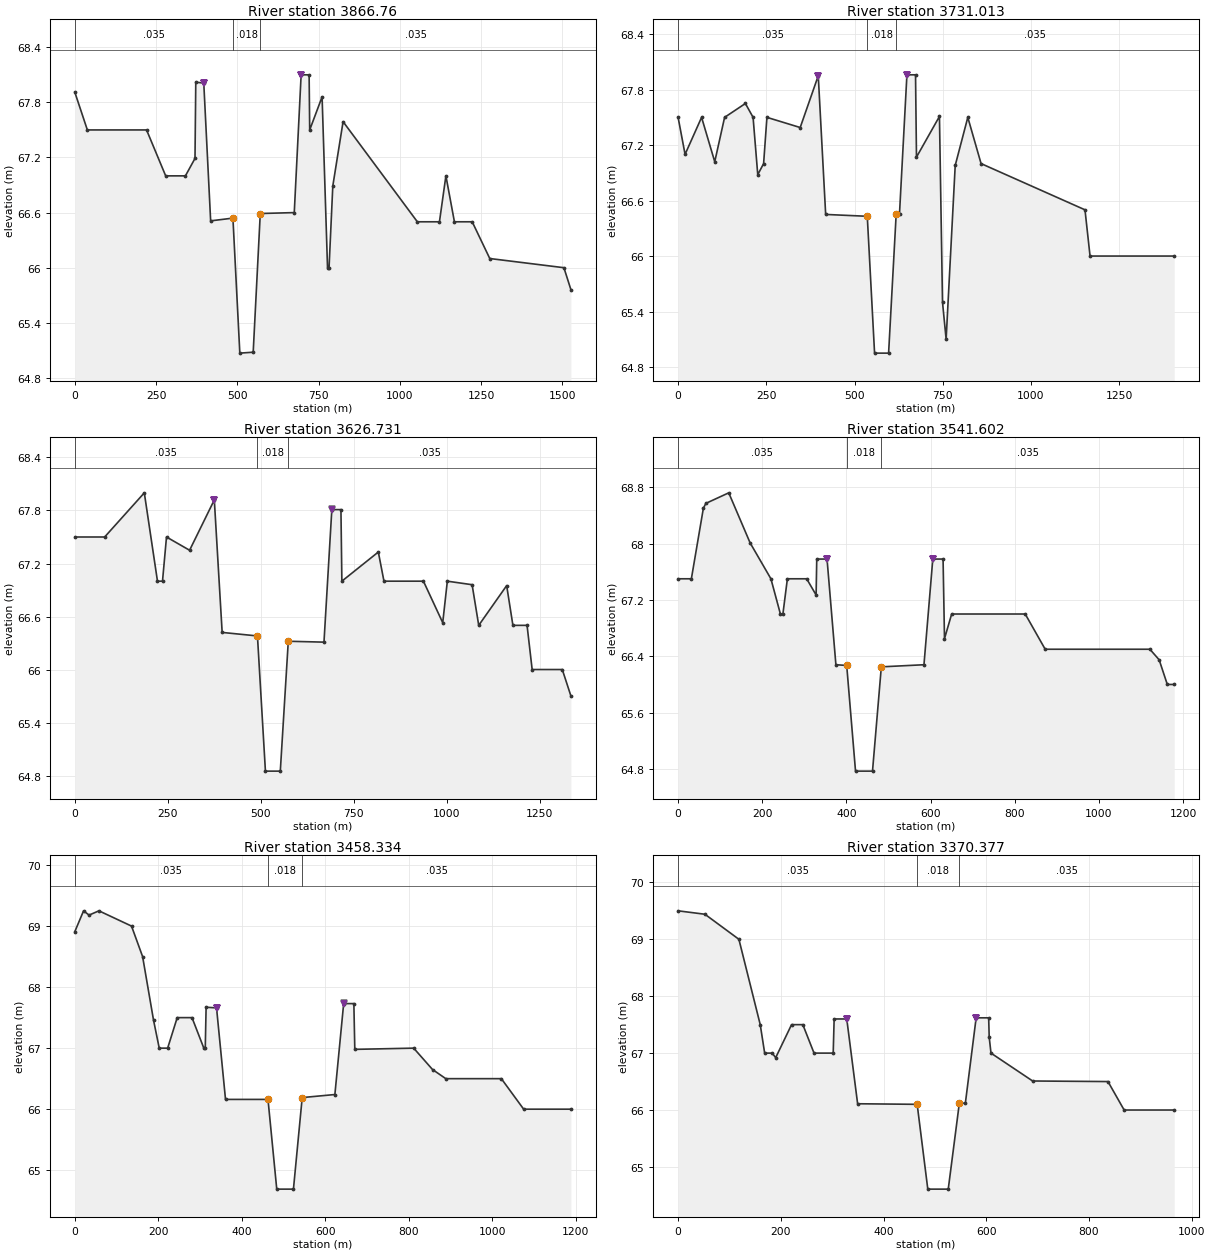
Type RM Length L Ch R = 1 ,3866.76 ,97.63,135.75,173.54
XS GIS Cut Line= 6
     1075756.633    1572841.4556    1075690.9219    1573207.6782
    1075669.0029    1573284.6865     1075751.079    1573369.0688
    1075711.3641    1573514.6497    1075685.5129    1574319.7386
#Sta/Elev= 30
       0   67.91   38.47    67.5  220.65    67.5  279.46      67  340.19      67
  369.66   67.19  372.07   68.02  396.65   68.01   417.8   66.51  486.35   66.54
  507.57   65.07  548.72   65.08  570.49   66.59  675.08    66.6  696.21    68.1
  720.75    68.1  722.55    67.5  760.66   67.86  777.38      66  782.08      66
  793.63   66.89  825.25   67.59 1053.72    66.5 1121.74    66.5 1141.59      67
 1167.79    66.5  1222.5    66.5 1276.57    66.1 1504.65      66 1526.26   65.76
#Mann= 3 , 0 , 0
       0    .035       0  486.35    .018       0  570.49    .035       0
Levee=-1,396.65,68.01249,-1,696.21,68.0983,	452,	451
Bank Sta=486.35,570.49
XS Rating Curve= 0 ,0
Exp/Cntr=0.3,0.1

Type RM Length L Ch R = 1 ,3731.013,59.63,104.28,148.99
XS GIS Cut Line= 5
    1075689.3229    1572830.0256     1075634.901    1573198.8102
    1075614.3722    1573360.8447    1075592.9913    1573495.9114
    1075549.9401    1574227.6634
#Sta/Elev= 30
       0    67.5   19.76    67.1   66.56    67.5  103.84   67.02  131.76    67.5
   190.7   67.65   212.5    67.5  225.73   66.88  242.34      67  251.72    67.5
  346.01   67.39  397.19   67.95   418.2   66.45  536.11   66.43  556.78   64.95
  596.55   64.95  618.12   66.46  627.46   66.46  648.46   67.96  672.86   67.96
  675.55   67.07  740.63   67.51  749.32    65.5  759.58    65.1  785.32   66.98
  821.01    67.5  858.59      67 1153.07    66.5 1167.43      66 1405.87      66
#Mann= 3 , 0 , 0
       0    .035       0  536.11    .018       0  618.12    .035       0
Levee=-1,397.19,67.95077,-1,648.45,67.95578,	452,	451
Bank Sta=536.11,618.12
XS Rating Curve= 0 ,0
Exp/Cntr=0.3,0.1

Type RM Length L Ch R = 1 ,3626.731,129.79,85.13,40.45
XS GIS Cut Line= 6
    1075627.4103    1572844.6306    1075607.1429    1573194.4161
    1075598.2002    1573311.9916    1075498.3482    1573345.6608
      1075481.36    1573355.1716    1075441.9899    1574094.3131
#Sta/Elev= 30
       0    67.5   80.12    67.5   186.7      68  222.09      67  235.59      67
  246.34    67.5  308.41   67.35  374.85   67.92  395.92   66.42  490.79   66.38
  512.21   64.85  552.21   64.85  573.66   66.32   669.6   66.31  690.69   67.81
  715.19   67.81  717.68      67  815.66   67.33  830.81      67  936.88      67
  988.77   66.53 1001.12      67 1067.72   66.96 1085.51    66.5 1160.62   66.95
 1177.38    66.5 1215.41    66.5 1229.11      66 1310.09      66 1333.33    65.7
#Mann= 3 , 0 , 0
       0    .035       0  490.79    .018       0  573.66    .035       0
Levee=-1,374.85,67.91953,-1,690.69,67.81227,	452,	451
Bank Sta=490.79,573.66
XS Rating Curve= 0 ,0
Exp/Cntr=0.3,0.1

Type RM Length L Ch R = 1 ,3541.602,126.01,83.27,40.5
XS GIS Cut Line= 5
    1075535.9701    1572849.7106    1075492.6232    1573176.2878
    1075477.1842    1573245.7481    1075441.3828     1573471.912
    1075373.4098     1574016.843
#Sta/Elev= 30
       0    67.5   31.53    67.5   60.02    68.5   65.89   68.57  120.34   68.72
  171.08   68.01  220.52    67.5  243.08      67  249.02      67  259.66    67.5
  305.49    67.5  327.91   67.27  329.44   67.78  353.89   67.78  374.93   66.28
   400.6   66.27  421.58   64.77  461.92   64.77  482.88   66.25  584.18   66.28
  605.18   67.78  629.58   67.78  632.97   66.65     650      67  824.78      67
   872.2    66.5 1120.97    66.5 1143.02   66.35 1162.39      66 1178.73      66
#Mann= 3 , 0 , 0
       0    .035       0   400.6    .018       0  482.88    .035       0
Levee=-1,353.89,67.78058,-1,605.18,67.77722,	452,	451
Bank Sta=400.6,482.88
XS Rating Curve= 0 ,0
Exp/Cntr=0.3,0.1

Type RM Length L Ch R = 1 ,3458.334,45.21,87.96,130.7
XS GIS Cut Line= 6
      1075468.66    1572854.7906    1075397.7402     1573161.268
    1075350.5497    1573280.2415    1075429.7808    1573344.9978
    1075402.6022    1573465.7731    1075323.8797    1573980.0129
#Sta/Elev= 30
       0   68.91   20.91   69.25   34.05   69.18   57.75   69.25  135.83      69
   162.4    68.5  188.54   67.46  202.25      67  222.42      67  245.32    67.5
  280.79    67.5   309.1      67  312.56      67  314.58   67.67  339.58   67.66
   361.1   66.16  462.89   66.16  483.89   64.69  523.89   64.69  544.89   66.19
   623.2   66.24  644.24   67.73  668.69   67.73  670.95   66.98  812.08      67
  857.18   66.65  889.04    66.5 1022.19    66.5 1075.62      66 1188.92      66
#Mann= 3 , 0 , 0
       0    .035       0  462.89    .018       0  544.89    .035       0
Levee=-1,339.58,67.66425,-1,644.24,67.73342,	452,	451
Bank Sta=462.89,544.89
XS Rating Curve= 0 ,0
Exp/Cntr=0.3,0.1

Type RM Length L Ch R = 1 ,3370.377,105.01,116.93,129.01
XS GIS Cut Line= 5
    1075430.5599    1572862.4107    1075337.9403    1573151.8017
    1075332.7697    1573282.7815    1075306.2176    1573450.5156
    1075204.4994    1573797.1325
#Sta/Elev= 27
       0    69.5   52.22   69.44  118.38      69  159.94    67.5  168.56      67
  183.23      67  190.02   66.92  220.92    67.5  242.88    67.5  264.69      67
  302.03      67  303.85    67.6  328.42    67.6  349.57   66.11  465.52    66.1
  486.21   64.61  526.04   64.61  547.63   66.12  559.36   66.12  580.36   67.62
  604.76   67.62  605.77   67.28  609.25      67  690.35   66.51  837.05    66.5
  868.54      66  965.99      66
#Mann= 3 , 0 , 0
       0    .035       0  465.52    .018       0  547.63    .035       0
Levee=-1,328.42,67.60355,-1,580.36,67.6181,	452,	451
Bank Sta=465.52,547.63
XS Rating Curve= 0 ,0
Exp/Cntr=0.3,0.1

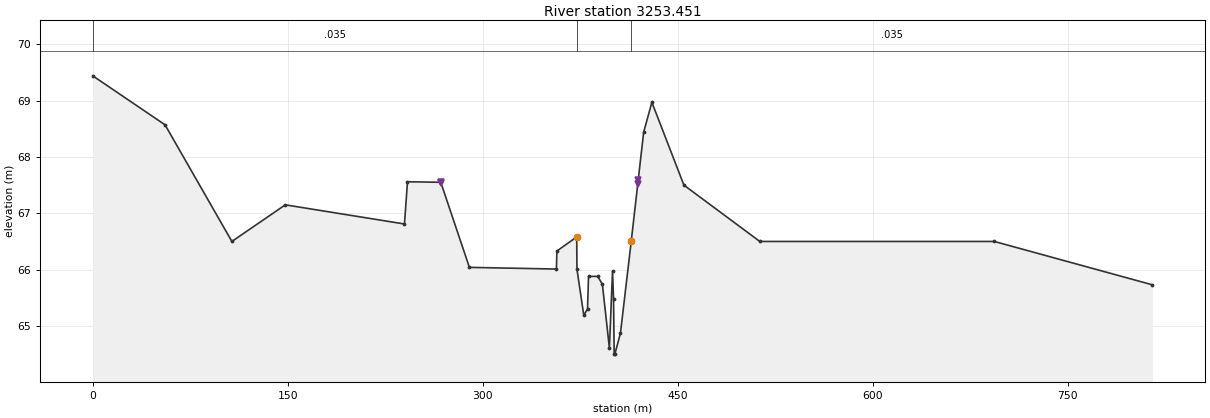
Type RM Length L Ch R = 1 ,3253.451,3151.83,3253.45,3107.68
XS GIS Cut Line= 4
    1075376.9439    1572916.6924    1075314.3958    1573116.1355
    1075171.5789    1573401.7692    1075008.1404    1573637.4453
#Sta/Elev= 30
       0   69.44   55.61   68.57  107.01    66.5  148.11   67.15  239.77   66.81
  242.11   67.56  267.71   67.55  289.73   66.04  356.68   66.01  357.02   66.33
  372.28   66.58  372.46   66.01  377.72   65.19   380.6    65.3  381.37   65.88
  388.47   65.88  392.03   65.74  397.42   64.61  399.83   65.97  400.63   65.47
   401.1   64.51  401.61    64.5  405.92   64.87  414.21    66.5  423.79   68.44
   430.1   68.97  454.75    67.5  513.14    66.5  693.52    66.5  815.17   65.73
#Mann= 3 , 0 , 0
       0    .035       0  372.28    .018       0  414.21    .035       0
Levee=-1,267.7,67.54605,-1,419.57,67.52,	452,
Bank Sta=372.28,414.21
XS Rating Curve= 0 ,0
Exp/Cntr=0.3,0.1
LCMann Table=0